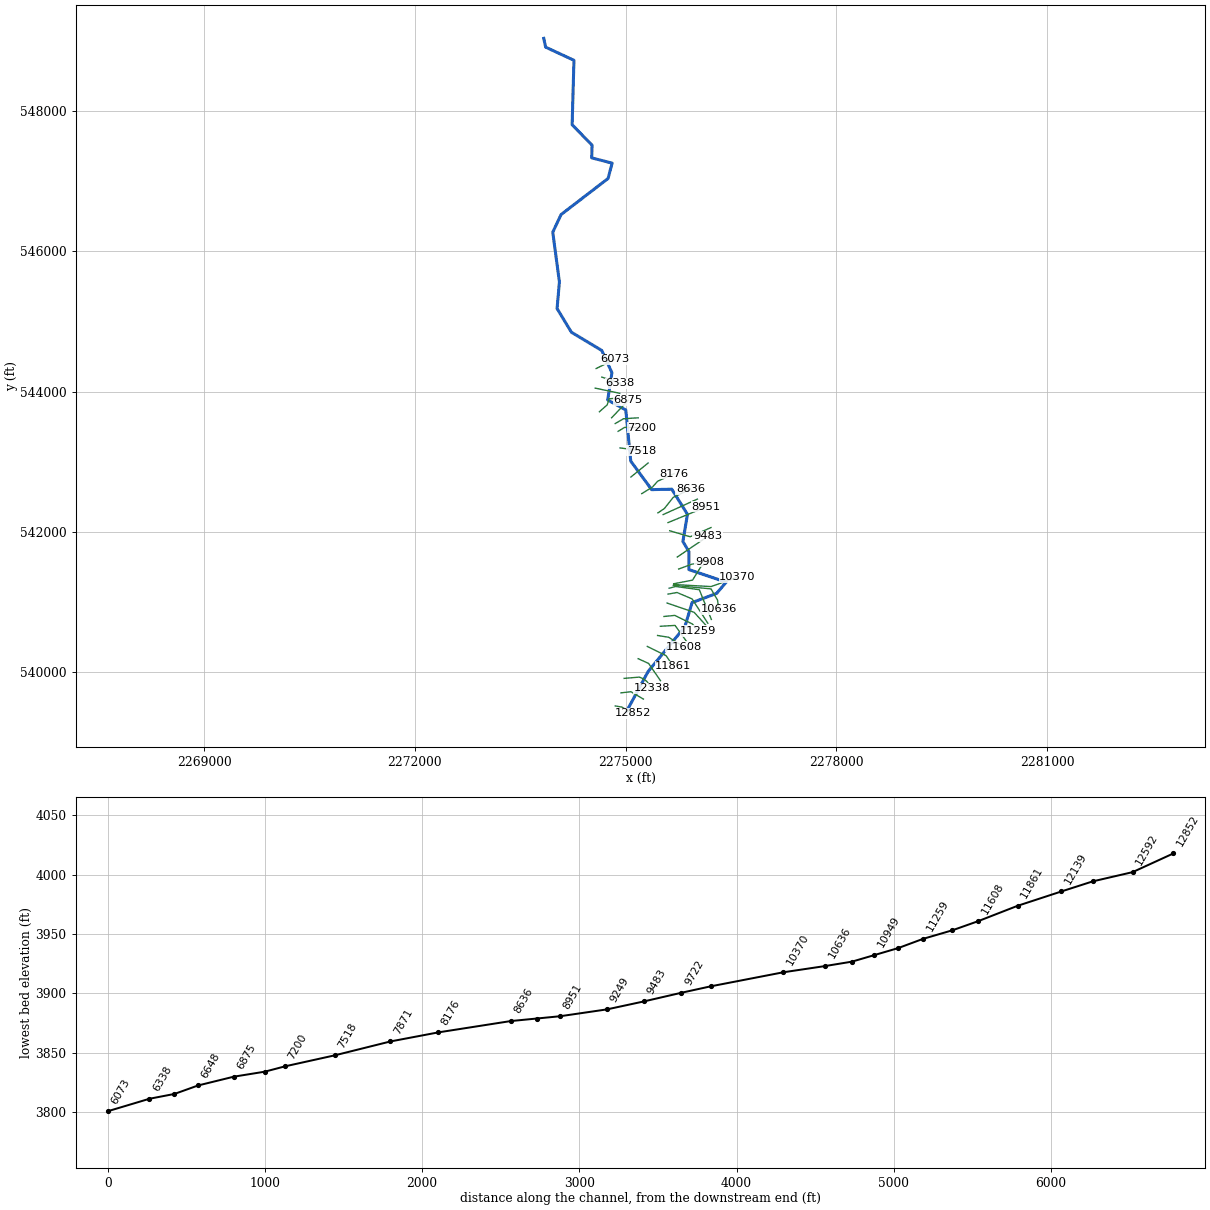
--- SECONDFK.prj (project) ---

Proj Title=SECONDFK
Current Plan=p01
Default Exp/Contr=0,0
English Units
Geom File=g01
Flow File=f01
Plan File=p01
Background Map Layer=Inundation Boundary (01pct Value_0)
Background Map Layer=QC
BEGIN DESCRIPTION:
Stream Name: Second Fork
Flood Zone: Approximate
Pocahontas County, WV
HEC-RAS Version: RAS 6.1.0
Vertical Datum: NAVD88
Projection: NAD 1983 StatePlane West Virginia S FIPS 4702 (US Feet)
Terrain: 1-meter LIDAR (FEMA Region III 3DEP collected 2016-2018)
Land Use: 2019 NLCD
Hydrologic Method:
WV SIR2010-5033 regression equations
END DESCRIPTION:
DSS Export Rating Curves= 0
DSS Export Rating Curve Sorted= 0
DSS Export Volume Flow Curves= 0
DXF OffsetX= 0
DXF OffsetY= 0
DXF ScaleX= 0
DXF ScaleY= 0

--- SECONDFK.p01 (plan) ---

Plan Title=Floodplain
Program Version=6.00
Short Identifier=Floodplain
Geom File=g01
Flow File=f01
Subcritical Flow
K Sum by GR= 0
Std Step Tol= 0.01
Critical Tol= 0.01
Num of Std Step Trials= 20
Max Error Tol= 0.3
Flow Tol Ratio= 0.001
Split Flow NTrial= 30
Split Flow Tol= 0.02
Split Flow Ratio= 0.02
Log Output Level= 0
Friction Slope Method= 1
Unsteady Friction Slope Method= 2
Unsteady Bridges Friction Slope Method= 1
Parabolic Critical Depth
Global Vel Dist= 0 , 0 , 0
Global Log Level= 0
CheckData=False
Encroach Param=-1 ,0,0, 0
Mapping Interval=1HOUR
Computation Time Step Use Courant=        0
Computation Time Step Use Time Series=    0
Computation Time Step Count To Double=0
Computation Time Step Max Doubling=0
Computation Time Step Max Halving=0
Computation Time Step Residence Courant=0
Run HTab= 0
Run UNet= 0
Run Sediment= 0
Run PostProcess= 0
Run WQNet= 0
Run RASMapper=-1
UNET Theta= 0
UNET Theta Warmup= 0
UNET ZTol= 0
UNET ZSATol= 0
UNET MxIter= 0
UNET Max Iter WO Improvement= 0
UNET MaxInSteps= 0
UNET DtIC= 0
UNET DtMin= 0
UNET MaxCRTS= 0
UNET WFStab= 0
UNET SFStab= 0
UNET WFX= 1
UNET SFX= 1
UNET Gravity=32.174
UNET 1D Methodology=Finite Difference
UNET DSS MLevel= 1
UNET Pardiso=0
UNET DZMax Abort= 0
UNET Use Existing IB Tables= 0
UNET Froude Reduction=False
UNET Froude Limit= 0
UNET Froude Power= 0
UNET D1 Cores= 0
UNET WindReference=Eulerian
UNET WindDragFormulation=Hsu (1988)
UNET D2 Coriolis=0
UNET D2 Cores= 0
UNET D2 Theta= 1
UNET D2 Theta Warmup= 1
UNET D2 Z Tol= 0.01
UNET D2 Volume Tol= 0.01
UNET D2 Max Iterations= 20
UNET D2 Equation= 0
UNET D2 RampUpFraction=0.1
UNET D2 TimeSlices= 1
UNET D2 Turbulence Formulation=Non-Conservative (original)
UNET D2 Eddy Viscosity=0.3
UNET D2 Transverse Eddy Viscosity=0.1
UNET D2 Smagorinsky Mixing=0
UNET D2 BCVolumeCheck=0
UNET D2 Cores=0
UNET D2 SolverType=PARDISO (Direct)
UNET D2 Minimum Iterations= 2147483647
UNET D2 Maximum Iterations= 2147483647
UNET D2 Restart Number= 10
UNET D2 Relaxation Coeff=1.3
UNET D2 SOR Precondition Iterations= 10
UNET D2 ILUT Maximum Fill= 8
UNET D2 ILUT Tolerance=1E-08
UNET D1D2 MaxIter= 0
UNET D1D2 ZTol=0.01
UNET D1D2 QTol=0.1
UNET D1D2 MinQTol=1
Write IC File= 0
Write IC File at Fixed DateTime=0
Write IC File at Sim End=0
Echo Input=False
Echo Parameters=False
Echo Output=False
Write Detailed= 0
HDF Write Warmup=0
HDF Write Time Slices=0
HDF Flush=0
HDF Compression= 1
HDF Chunk Size= 1
HDF Spatial Parts= 1
HDF Use Max Rows=0
HDF Fixed Rows= 1
Calibration Method= 0
Calibration Iterations= 20
Calibration Max Change=0.05
Calibration Tolerance=0.2
Calibration Maximum=1.5
Calibration Minimum=0.5
Calibration Optimization Method= 1
WQ AD Non Conservative
WQ ULTIMATE=-1
WQ Max Comp Step=1HOUR
WQ Output Interval=15MIN
WQ Output Selected Increments= 0
WQ Output face flow=0
WQ Output face velocity=0
WQ Output face area=0
WQ Output face dispersion=0
WQ Output cell volume=0
WQ Output cell surface area=0
WQ Output cell continuity=0
WQ Output cumulative cell continuity=0
WQ Output face conc=0
WQ Output face dconc_dx=0
WQ Output face courant=0
WQ Output face peclet=0
WQ Output face adv mass=0
WQ Output face disp mass=0
WQ Output cell mass=0
WQ Output cell source sink temp=0
WQ Output nsm pathways=0
WQ Output nsm derived pathways=0
WQ Create Restart=0
WQ Fixed Restart=0
WQ System Summary=0
WQ Write To DSS=0
Sorting and Armoring Iterations= 10
XS Update Threshold= 0.02
Bed Roughness Predictor= 0
Hydraulics Update Threshold= 0.02
Energy Slope Method= 1
Volume Change Method= 1
Sediment Retention Method= 0
Sediment TS Multiplier= 1
Warm Up Method= 0
XS Weighting Method= 0
Number of US Weighted Cross Sections= 1
Number of DS Weighted Cross Sections= 1
Upstream XS Weight=0
Main XS Weight=1
Downstream XS Weight=0
Number of DS XS's Weighted with US Boundary= 1
Upstream Boundary Weight= 1
Weight of XSs Associated with US Boundary= 0
Number of US XS's Weighted with DS Boundary= 1
Downstream Boundary Weight= 0.5
Weight of XSs Associated with DS Boundary= 0.5
Percentile Method= 0
Sediment Output Level= 3
Mass or Volume Output= 0
Output Increment Type= 1
Profile and TS Output Increment= 1
Transport Output Increment 1
XS Output Flag= 0
XS Output Increment= 10
Read HDF5 Sediment Hotstart= 0
Sediment Hotstart Type= 0
Write Gradation File= 0
Read Gradation Hotstart= 0
Write HDF5 File= 1
Write Binary Output= 1
Write DSS Sediment File= 0
DSS Sediment Output Type= 1
SV Curve= 0
Specific Gage Flag= 0
Subcell Erosion Methods= 0
Subcell Deposition Methods= 0
Advection Scheme= 1
Matrix Solver= 0
Implicit Weighting Factor= 1
Maximum Outer Loop Convergence Iterations= 5
Convergence Maximum Absolute= 0.001
Convergence RMSE= 0.0001
Grain Fractions Max Abs Error= 0.001
Max Subgrid Regions= 1
Max Subgrid Length Scale= 3.402823E+38
Initial Layer Thickness= 3.402823E+38
Min Layer Thickness= 3.402823E+38
Max Layer Thickness= 3.402823E+38
Number of Layers= 5

--- SECONDFK.f01 (steady flow) ---

Flow Title=USGS Regression Equation
Program Version=6.10
Number of Profiles= 6
Profile Names=01pct,10pct,04pct,02pct,0_2pct,01plus
River Rch & RM=SECONDFK,Main            ,12852
     816     437     577     693    1130    1210
River Rch & RM=SECONDFK,Main            ,9249
    1030     554     729     873    1420    1520
River Rch & RM=SECONDFK,Main            ,5602
    1160     628     824     985    1590    1710
River Rch & RM=SECONDFK,Main            ,3310
    1290     704     923    1100    1780    1910
Boundary for River Rch & Prof#=SECONDFK,Main            , 1
Up Type= 0
Dn Type= 3
Dn Slope=0.008
Boundary for River Rch & Prof#=SECONDFK,Main            , 2
Up Type= 0
Dn Type= 3
Dn Slope=0.008
Boundary for River Rch & Prof#=SECONDFK,Main            , 3
Up Type= 0
Dn Type= 3
Dn Slope=0.008
Boundary for River Rch & Prof#=SECONDFK,Main            , 4
Up Type= 0
Dn Type= 3
Dn Slope=0.008
Boundary for River Rch & Prof#=SECONDFK,Main            , 5
Up Type= 0
Dn Type= 3
Dn Slope=0.008
Boundary for River Rch & Prof#=SECONDFK,Main            , 6
Up Type= 0
Dn Type= 3
Dn Slope=0.008
DSS Import GetInterval= 0
DSS Import GetPeak= 0
DSS Import FillOption= 0

--- SECONDFK.g01 (geometry) ---

Geom Title=Geometry
Program Version=6.10

River Reach=SECONDFK        ,Main
Reach XY= 30
     2275014.633      539448.728     2275319.783      540014.208
     2275842.271      540650.669     2275945.434      540995.579
     2276293.963      541126.053     2276431.356      541286.807
     2275899.318      541465.531     2275901.317      541719.058
     2275814.572      541865.6672275879.41729886542252.749313224
     2275656.489      542610.452     2275370.074      542604.056
     2275072.416      543010.1532275001.77082696543738.615759698
     2274744.264      543880.724     2274804.654      544269.097
     2274660.338       544585.81     2274227.688      544845.696
     2274023.846      545183.134     2274057.298      545561.768
2273962.47431379546270.159751823     2274081.051      546521.627
     2274749.945      547035.249     2274807.212      547253.576
     2274516.776      547328.876     2274521.934      547509.005
     2274238.219      547800.905     2274264.247      548718.082
     2273860.965      548905.629     2273834.059      549031.012

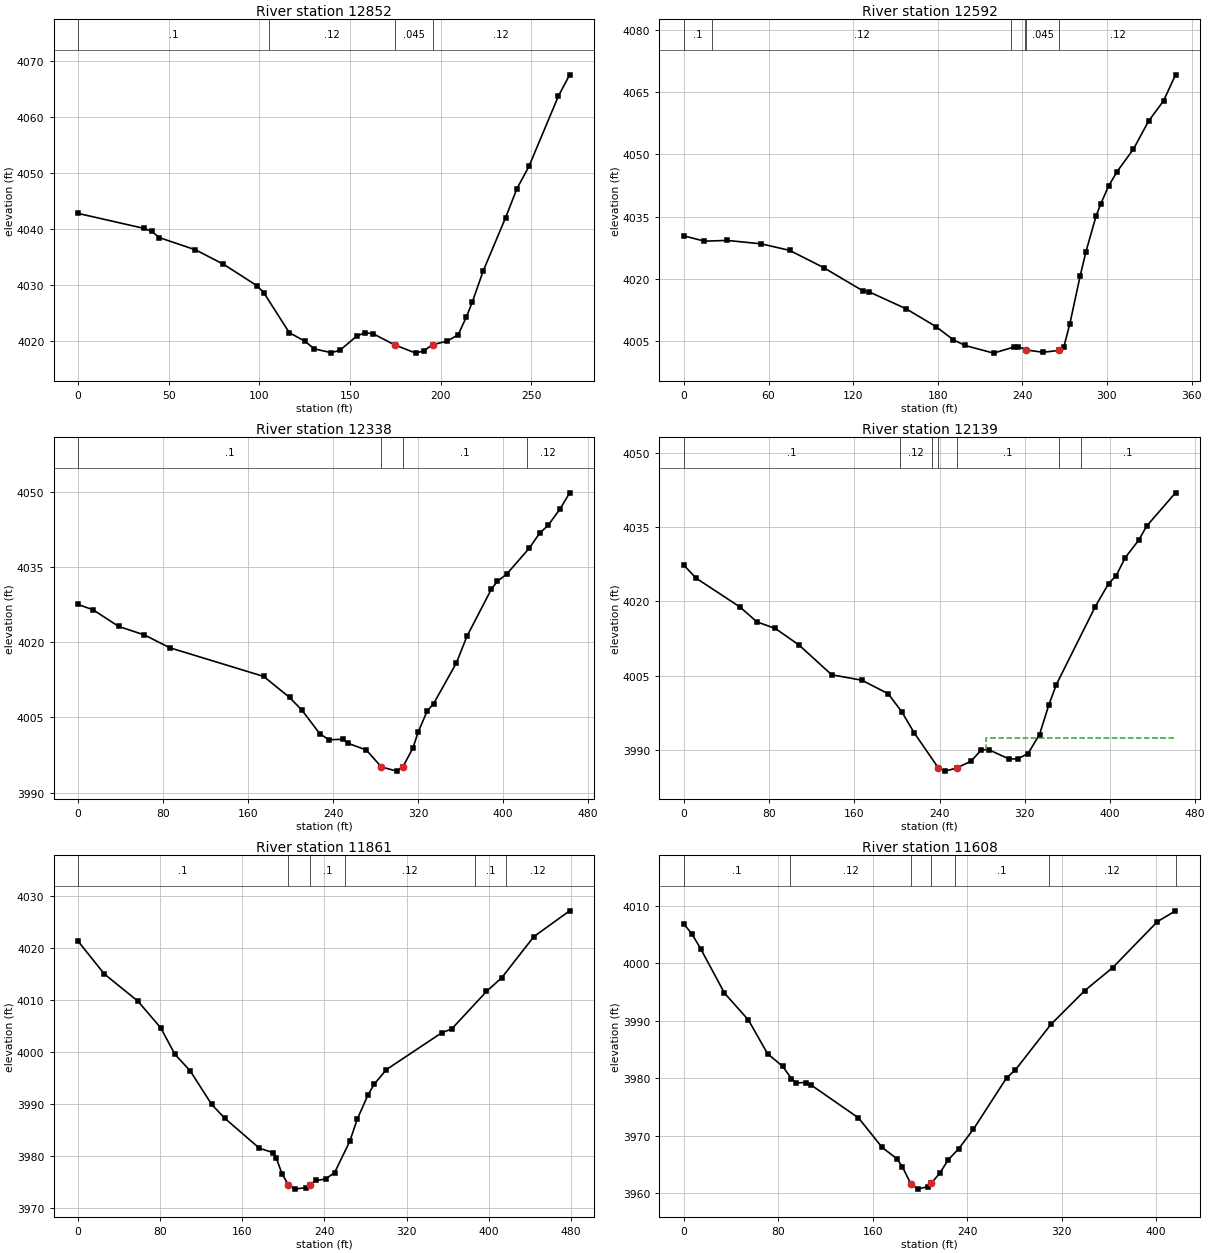
Type RM Length L Ch R = 1 ,12852   ,260.2,260.2,260.2
XS GIS Cut Line= 3
2274852.03969135539523.5501196822274945.85727513539507.742159723
2275097.13368289539417.719149097
#Sta/Elev= 30
       0 4042.79    36.6  4040.1    40.7 4039.57    44.8 4038.47    64.7  4036.3
    80.2 4033.72    98.7 4029.88   102.5 4028.61   116.5 4021.51     125    4020
   130.4  4018.6   139.6 4017.94   144.4 4018.34   153.7 4020.88   158.3  4021.5
   162.9 4021.29   174.6 4019.33   186.3 4017.85   190.9  4018.3   195.6 4019.35
   203.8 4020.01   209.7 4021.14   214.2 4024.29   217.5 4026.96   223.5 4032.52
   235.9 4042.06   242.1  4047.2   248.8 4051.22     265 4063.74   271.2 4067.53
#Mann= 4 ,-1,0
       0      .1       0  105.14     .12       0   174.6    .045       0
   195.6     .12       0
Bank Sta=174.6,195.6
XS Rating Curve= 0 ,0
Exp/Cntr(USF)=0,0
Exp/Cntr=0.3,0.1

Type RM Length L Ch R = 1 ,12592   ,254.8,253.5,252.9
XS GIS Cut Line= 3
 2274933.7932366539709.8267208342275074.76016258539726.168692832
2275252.54811918539620.846313909
#Sta/Elev= 30
       0 4030.35    14.5 4029.07    30.6 4029.25    54.7 4028.43    74.9 4026.85
      99  4022.7   127.2 4017.02   131.5 4016.81   157.5 4012.76   178.7 4008.47
   190.9 4005.31   199.3 4003.91   219.6 4002.06   234.4 4003.57   237.1 4003.61
   242.9 4002.82   254.6 4002.27   266.3 4002.72   269.4 4003.53   273.7 4009.19
   280.9 4020.55   285.1 4026.55   292.3 4035.16   295.5 4038.01   301.3 4042.46
   307.2 4045.87   318.8  4051.3   329.5 4058.03   340.1 4062.91   348.6  4069.2
#Mann= 6 ,-1,0
       0      .1       0      20     .12       0  231.91      .1       0
  241.91     .12       0   242.9    .045       0   266.3     .12       0
Bank Sta=242.9,266.3
XS Rating Curve= 0 ,0
Exp/Cntr(USF)=0,0
Exp/Cntr=0.3,0.1

Type RM Length L Ch R = 1 ,12338   ,204.8,199.8,195.2
XS GIS Cut Line= 5
2274978.16349421539916.1421406242275194.96934989539934.388177982
2275241.74521838539914.6652364632275302.43753657539872.533014681
2275371.89145047 539774.10771102
#Sta/Elev= 30
       0 4027.53    14.2 4026.45    38.1 4023.15    62.4 4021.45    86.3 4018.89
   174.6 4013.18   199.1 4008.97   210.8 4006.42   227.6 4001.71   236.2 4000.53
   249.3 4000.64   253.6 3999.87   271.3 3998.49   285.5 3995.11   299.9 3994.28
   305.6  3995.1   315.1 3998.84     320 4002.02   328.6 4006.27   334.6 4007.73
   356.1 4015.87     366 4021.17   388.9 4030.53   394.7 4032.16   403.3 4033.55
   424.7 4038.76   434.4 4041.73   442.4 4043.31     454 4046.67   462.7  4049.8
#Mann= 4 ,-1,0
       0      .1       0   285.5    .045       0   305.6      .1       0
  422.22     .12       0
Bank Sta=285.5,305.6
XS Rating Curve= 0 ,0
Exp/Cntr(USF)=0,0
Exp/Cntr=0.3,0.1

Type RM Length L Ch R = 1 ,12139   ,269.9,278.2,284.5
XS GIS Cut Line= 3
2275177.82202922540196.3571750582275325.87071508540129.248343897
2275495.85164622539883.202564162
#Sta/Elev= 30
       0 4027.29    11.4  4024.7    52.5  4018.9    68.5 4015.88    85.8 4014.55
     108 4011.22   138.7 4005.21   167.1 4004.11   191.8 4001.38   204.5 3997.76
     216 3993.56     239 3986.39   245.3 3985.77   256.3 3986.41   269.6 3987.78
   279.3 3990.06   286.2  3990.1   305.1 3988.23   313.3 3988.24   323.1 3989.32
   333.9 3993.16   342.5 3999.03   349.6 4003.19   386.3 4018.98   398.8 4023.62
   405.9 4025.21   414.4 4028.85     427 4032.35   434.5 4035.21   461.6 4041.92
#Mann= 7 ,-1,0
       0      .1       0  202.55     .12       0  232.55      .1       0
     239    .045       0   256.3      .1       0  352.55     .12       0
  372.55      .1       0
#XS Ineff= 2 , 0
                          283.23         3992.48
Permanent Ineff=
       F       F
Bank Sta=239,256.3
XS Rating Curve= 0 ,0
Exp/Cntr(USF)=0,0
Exp/Cntr=0.3,0.1

Type RM Length L Ch R = 1 ,11861   ,254.4,252.2,251.2
XS GIS Cut Line= 3
2275307.87918144540371.0034059412275574.14573181540240.287024144
2275678.63734169540091.062683536
#Sta/Elev= 30
       0 4021.29    25.5 4015.01    58.3 4009.77    80.5 4004.66    94.2 3999.61
   109.2  3996.4   130.1 3989.96   142.9 3987.29   176.6 3981.55   189.9 3980.71
   192.9 3979.73   198.8 3976.57   204.8 3974.54   210.8  3973.7     222 3973.99
   225.7 3974.57   231.7 3975.36     241 3975.63   249.9 3976.89   264.6 3982.87
   272.1 3987.22   282.5 3991.83   288.5 3993.87   300.4 3996.66   354.1 4003.71
   363.9 4004.45   397.8 4011.65   412.7  4014.3   443.9 4022.17   478.8 4027.13
#Mann= 6 ,-1,0
       0      .1       0   204.8    .045       0   225.7      .1       0
     260     .12       0  386.62      .1       0  416.62     .12       0
Bank Sta=204.8,225.7
XS Rating Curve= 0 ,0
Exp/Cntr(USF)=0,0
Exp/Cntr=0.3,0.1

Type RM Length L Ch R = 1 ,11608   ,168.3,161.9,157.6
XS GIS Cut Line= 3
2275454.27540652540527.014820292 2275611.5191604540501.804198788
2275829.18842988540365.032487446
#Sta/Elev= 30
       0 4006.84     6.8 4005.13    14.1 4002.58    34.3 3994.84    54.6 3990.15
    70.8 3984.28    83.6 3982.08      91 3979.95    95.1 3979.21   103.2 3979.26
   107.3 3978.88   147.8  3973.1   167.9 3967.95   180.5 3965.95   184.8 3964.63
   192.1 3961.66   197.8 3960.69   206.6 3961.13   209.5 3961.71   216.7 3963.49
     224 3965.84   232.7 3967.72   245.1 3971.11   273.3 3980.08   280.7 3981.46
   310.8 3989.39   339.5 3995.28   363.2 3999.29     401 4007.29   416.3 4009.17
#Mann= 7 ,-1,0
       0      .1       0      90     .12       0   192.1    .045       0
   209.5     .12       0  229.25      .1       0  309.25     .12       0
  416.32      .1       0
Bank Sta=192.1,209.5
XS Rating Curve= 0 ,0
Exp/Cntr(USF)=0,0
Exp/Cntr=0.3,0.1

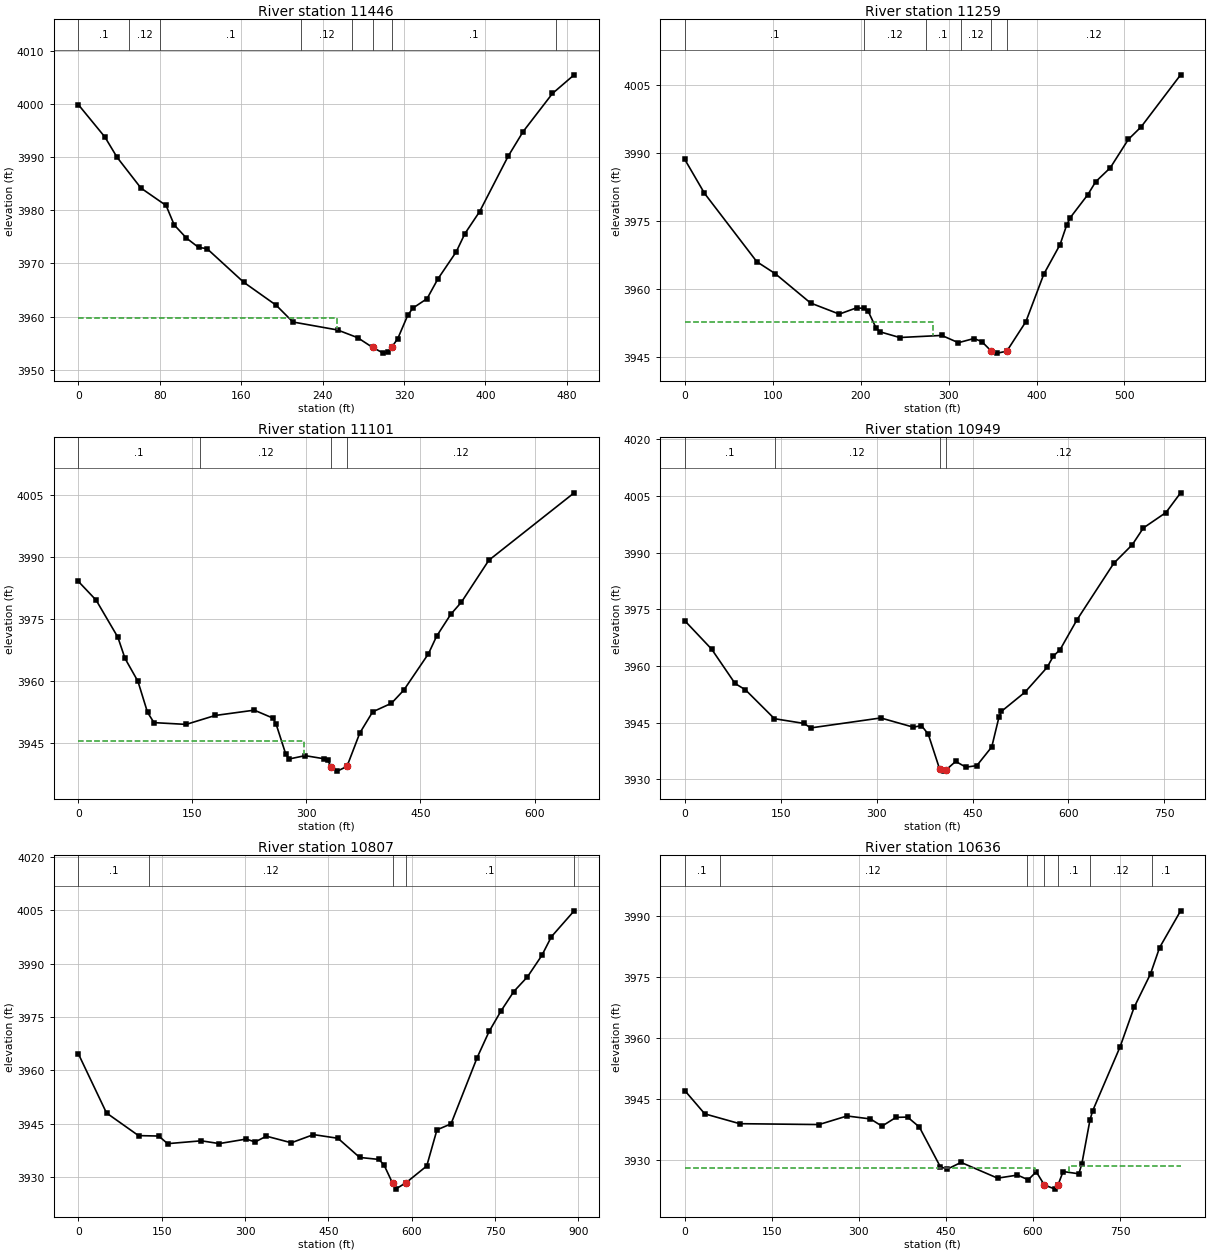
Type RM Length L Ch R = 1 ,11446   ,179.9,187.3,193.6
XS GIS Cut Line= 3
2275494.12096184540658.2826208362275702.75341736540670.253335496
2275865.21311632540444.519859037
#Sta/Elev= 30
       0  3999.9    26.1  3993.8    38.1 3989.97    61.5 3984.19    86.2 3980.91
    94.2 3977.25   106.2 3974.77   118.2    3973   126.3  3972.8   162.3 3966.48
   194.4 3962.12   210.8 3958.97   254.7 3957.47   274.4 3956.02   289.2 3954.17
   299.6 3953.11   303.9 3953.29   308.2 3954.32   313.8 3955.84   323.6 3960.23
   328.6 3961.58   342.6 3963.37   353.2 3967.07   371.2 3972.17   379.8 3975.62
   394.2 3979.75   422.2 3990.16     437 3994.83   465.8    4002   487.1 4005.51
#Mann= 8 ,-1,0
       0      .1       0      50     .12       0      80      .1       0
  218.98     .12       0  268.98      .1       0   289.2    .045       0
   308.2      .1       0  468.98     .12       0
#XS Ineff= 2 , 0
             254  3959.7
Permanent Ineff=
       F       F
Bank Sta=289.2,308.2
XS Rating Curve= 0 ,0
Exp/Cntr(USF)=0,0
Exp/Cntr=0.3,0.1

Type RM Length L Ch R = 1 ,11259   ,156.3,157.8,159.2
XS GIS Cut Line= 4
2275545.92610357540797.5973127372275698.97293423540813.192635916
2275950.73551678 540689.771245992276034.69043905540590.991998064
#Sta/Elev= 30
       0 3988.55    22.4 3981.08    81.9 3966.01   102.8 3963.38     143 3956.91
   175.7 3954.46   195.3 3955.84   204.2 3955.71   208.6 3955.07   217.5 3951.41
     222 3950.56   244.4  3949.3   292.3 3949.76   311.1 3948.16   328.9 3949.08
   337.8  3948.4   348.7 3946.28   355.6 3945.86   366.2 3946.29   387.9 3952.79
   408.3 3963.27   426.8 3969.79   434.2 3974.03   438.5 3975.75   458.4  3980.8
   467.3 3983.64   483.9 3986.71   504.4 3992.96     519 3995.73   563.9  4007.2
#Mann= 6 ,-1,0
       0      .1       0  203.84     .12       0  273.84      .1       0
  313.84     .12       0   348.7    .045       0   366.2     .12       0
#XS Ineff= 2 , 0
          282.67 3952.69
Permanent Ineff=
       F       F
Bank Sta=348.7,366.2
XS Rating Curve= 0 ,0
Exp/Cntr(USF)=0,0
Exp/Cntr=0.3,0.1

Type RM Length L Ch R = 1 ,11101   ,157.6,151.8,143.9
XS GIS Cut Line= 3
2275590.08058906540989.1600772762275974.85356029540856.798175172
2276139.53639198 540675.18533275
#Sta/Elev= 30
       0 3984.07    23.4 3979.52      52 3970.53    61.4  3965.4    78.4 3959.85
      91 3952.33    99.5 3949.85   141.8 3949.42   179.9 3951.58   231.4 3952.87
     256 3950.94   260.2 3949.44   272.9 3942.17   277.2 3941.04   298.3 3941.85
   322.7 3941.11   327.9 3940.73   332.3 3939.22   340.6  3938.1   353.3 3939.24
   370.2 3947.34   387.1 3952.46   411.8 3954.54     428 3957.71   460.4 3966.52
   471.2 3970.78   489.7 3976.06   503.9 3979.06   539.9 3989.19   652.1 4005.52
#Mann= 4 ,-1,0
       0      .1       0     160     .12       0   332.3    .045       0
   353.3     .12       0
#XS Ineff= 2 , 0
          296.17 3945.47
Permanent Ineff=
       F       F
Bank Sta=332.3,353.3
XS Rating Curve= 0 ,0
Exp/Cntr(USF)=0,0
Exp/Cntr=0.3,0.1

Type RM Length L Ch R = 1 ,10949   ,140.6,142.1,139.4
XS GIS Cut Line= 4
2275602.79733701541116.0563780422275731.18512422541139.193034356
2275945.61081448541047.6455689042276169.36823288540701.887832858
#Sta/Elev= 30
       0 3971.98      42 3964.46    78.6 3955.38    94.9  3953.7   140.2 3946.06
   186.5 3944.81   196.8 3943.62   306.5 3946.26   357.7 3943.81   370.1 3944.25
   380.8 3941.96   398.73932.668   404.7 3932.19   409.13932.596   423.7 3934.76
   439.6 3933.24   456.7 3933.64   480.1  3938.6   491.6 3946.64   495.2    3948
   532.1 3953.08   566.7 3959.65   576.2 3962.56   587.1 3964.37   613.1 3972.15
     671  3987.2   699.9  3992.1   717.2 3996.53   752.5 4000.61   775.5 4005.83
#Mann= 4 ,-1,0
       0      .1       0  140.46     .12       0   398.7    .045       0
   409.1     .12       0
Bank Sta=398.7,409.1
XS Rating Curve= 0 ,0
Exp/Cntr(USF)=0,0
Exp/Cntr=0.3,0.1

Type RM Length L Ch R = 1 ,10807   ,169.1,171.8,173.9
XS GIS Cut Line= 4
2275619.15232466541200.3576859312275712.37400118541224.698139075
2276048.72997077541178.468379123   2276219.56917540755.218110766
#Sta/Elev= 30
       0  3964.7    50.7 3948.07   108.3 3941.71   144.6 3941.59   160.7 3939.45
   221.3 3940.25   253.6 3939.47   302.1 3940.74   318.2 3939.93   338.4 3941.55
   383.3  3939.7   423.2 3941.99   467.2 3940.96   506.3 3935.58   540.9 3935.02
   550.1 3933.48   565.5 3928.34     571 3926.68   590.1 3928.52     627 3933.18
   645.4 3943.33   670.7 3945.01   717.6 3963.58   739.2 3970.95   760.8 3976.75
   783.7 3982.18   808.3 3986.31   834.1  3992.3   851.3 3997.56   892.3 4004.84
#Mann= 5 ,-1,0
       0      .1       0  126.35     .12       0   565.5    .045       0
   590.1      .1       0  892.29     .12       0
Bank Sta=565.5,590.1
XS Rating Curve= 0 ,0
Exp/Cntr(USF)=0,0
Exp/Cntr=0.3,0.1

Type RM Length L Ch R = 1 ,10636   ,249.4,265.8,283.7
XS GIS Cut Line= 4
2275677.88031489541241.4592206692276214.35049275541190.830456152
2276307.81898109541030.1814918212276324.37069256540901.662320357
#Sta/Elev= 30
       0  3947.1    34.4 3941.39    94.7 3938.98   231.3 3938.77   279.5 3940.87
   319.7 3940.15   339.8 3938.38   363.9 3940.53   383.8  3940.6   404.1 3938.17
   440.2 3928.44   452.3 3927.84     476 3929.49   538.9 3925.63   573.2 3926.38
   591.7 3925.23   605.6 3927.19   619.4 3923.97   637.9 3922.94  643.07 3923.96
   651.8 3927.25   678.9  3926.7   684.2 3929.21   698.1 3939.88   702.7 3942.12
   749.9 3957.79   774.1 3967.48   802.4  3975.7     818 3982.13   854.3 3991.16
#Mann= 7 ,-1,0
       0      .1       0      60     .12       0  588.85      .1       0
   619.4    .045       0  643.07      .1       0  698.85     .12       0
  804.72      .1       0
#XS Ineff= 2 , 0
          604.09 3928.19   662.4          3928.5
Permanent Ineff=
       F       F
Bank Sta=619.4,643.07
XS Rating Curve= 0 ,0
Exp/Cntr(USF)=0,0
Exp/Cntr=0.3,0.1

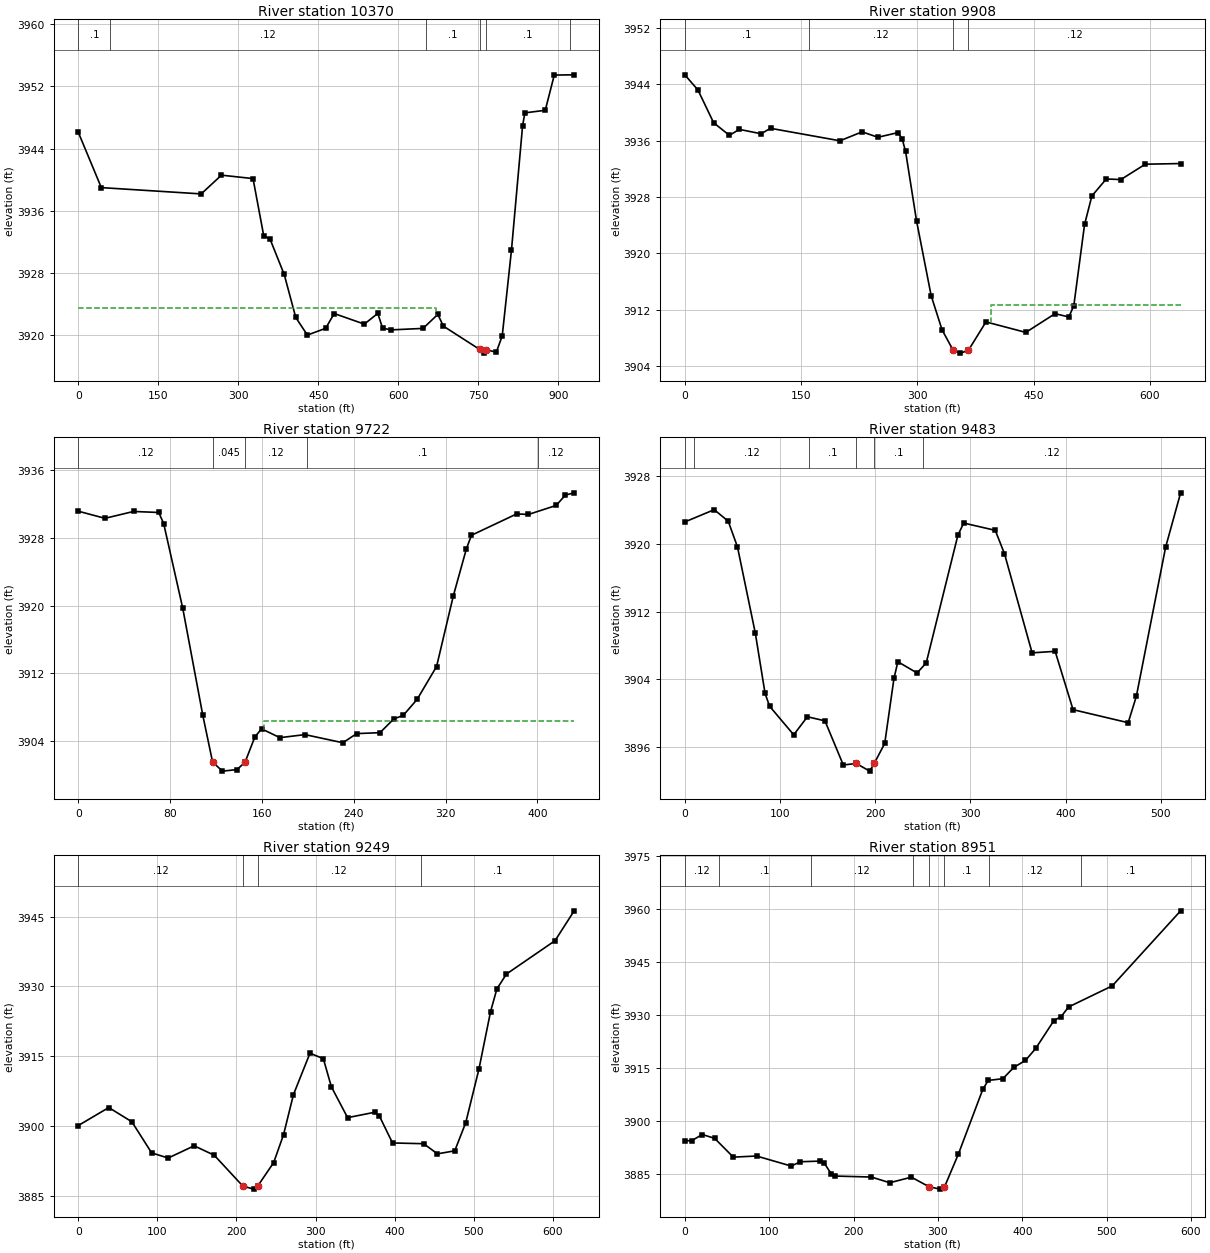
Type RM Length L Ch R = 1 ,10370   ,458,462.2,469.9
XS GIS Cut Line= 3
2275685.10740702541252.9151267672276215.43156007541223.558879373
2276591.36647769541356.376000341
#Sta/Elev= 30
       0 3946.08    43.1 3938.98   230.4 3938.17   268.4 3940.58   327.6 3940.14
   347.6 3932.82   359.8 3932.31   386.1 3927.81   407.7 3922.29   429.5 3920.02
   463.8 3920.89   479.8 3922.79   536.3 3921.43   561.6 3922.81   570.6  3920.9
   587.1 3920.69   646.5 3920.88   674.1 3922.68   684.6 3921.17   752.7 3918.17
     761  3917.7   765.3 3918.13   783.8 3917.82   794.9 3919.91   812.2 3930.91
   833.1 3946.94   837.4 3948.59   875.6 3948.92   892.5 3953.45   929.8 3953.48
#Mann= 6 ,-1,0
       0      .1       0      60     .12       0  651.14      .1       0
   752.7    .045       0   765.3      .1       0  921.14     .12       0
#XS Ineff= 2 , 0
          671.62  3923.5
Permanent Ineff=
       F       F
Bank Sta=752.7,765.3
XS Rating Curve= 0 ,0
Exp/Cntr(USF)=0,0
Exp/Cntr=0.3,0.1

Type RM Length L Ch R = 1 ,9908    ,197,185.3,174.6
XS GIS Cut Line= 4
  2275683.626534541263.3917115352275951.78829439541315.333550076
2276074.33481471541511.3430498722276190.66356571541580.413245774
#Sta/Elev= 30
       0 3945.34    16.9  3943.2    37.2 3938.54    57.6 3936.75    70.3  3937.6
    98.3 3936.98   110.6 3937.75   200.2 3935.98   228.7 3937.25   249.1 3936.48
   275.3 3937.15   280.6 3936.17   284.8 3934.47   298.9 3924.64   317.8    3914
   331.9 3909.14   346.1 3906.27   355.5 3905.85   365.8 3906.24   388.5 3910.28
   439.9 3908.79   477.6 3911.45   495.4 3910.98   501.8 3912.57   515.7 3924.11
   525.1 3928.15   543.7 3930.56   562.5 3930.48   594.1 3932.66   639.6 3932.75
#Mann= 4 ,-1,0
       0      .1       0     160     .12       0   346.1    .045       0
   365.8     .12       0
#XS Ineff= 2 , 0
                          394.76         3912.75
Permanent Ineff=
       F       F
Bank Sta=346.1,365.8
XS Rating Curve= 0 ,0
Exp/Cntr(USF)=0,0
Exp/Cntr=0.3,0.1

Type RM Length L Ch R = 1 ,9722    ,237.8,239.1,239.9
XS GIS Cut Line= 4
2275754.43074949541473.1726784532275941.22598164541542.314628731
2276041.89601249541557.7112216832276162.72462448541608.639934444
#Sta/Elev= 30
       0 3931.15    23.2 3930.31    48.1 3931.12    70.1    3931    74.4 3929.68
      91 3919.69   108.5 3907.04     117 3901.54   125.6 3900.47   138.3 3900.65
  145.31 3901.53   153.9 3904.52   159.7 3905.46   175.7 3904.42   197.5 3904.78
   230.5 3903.82   242.6  3904.9   262.9 3905.01     275 3906.64   283.1 3907.04
   295.2 3908.93   312.2 3912.82   326.8 3921.16   338.2 3926.72   342.6 3928.31
     382 3930.83   392.3 3930.77   416.4 3931.83   424.5 3933.06   432.1 3933.32
#Mann= 5 ,-1,0
       0     .12       0     117    .045       0  145.31     .12       0
  199.18      .1       0  401.02     .12       0
#XS Ineff= 2 , 0
                          161.74         3906.42
Permanent Ineff=
       F       F
Bank Sta=117,145.31
XS Rating Curve= 0 ,0
Exp/Cntr(USF)=0,0
Exp/Cntr=0.3,0.1

Type RM Length L Ch R = 1 ,9483    ,246.9,234.6,221.5
XS GIS Cut Line= 2
2275734.43674541541644.0305314732276165.21665143541936.670045688
#Sta/Elev= 30
       0 3922.59    30.9 3924.04    45.6 3922.68    55.3 3919.65    74.1 3909.44
    84.3 3902.34    89.1 3900.82   114.4 3897.45   128.8 3899.58   147.2  3899.1
   166.5 3893.88     180 3894.07   194.2 3893.16     1993894.077     210 3896.43
   219.7 3904.11   223.8 3906.08     244 3904.75   253.6 3905.95   286.8    3921
   292.9 3922.46   326.1  3921.6   335.8 3918.83   364.8 3907.13     389 3907.31
   407.8 3900.42   465.7 3898.88   474.3    3902     505 3919.59   520.8 3926.03
#Mann= 6 ,-1,0
       0      .1       0      10     .12       0     130      .1       0
     180    .045       0     199      .1       0     250     .12       0
Bank Sta=180,199
XS Rating Curve= 0 ,0
Exp/Cntr(USF)=0,0
Exp/Cntr=0.3,0.1

Type RM Length L Ch R = 1 ,9249    ,287.4,297.6,306.5
XS GIS Cut Line= 3
2275627.19617809542018.4636987292275918.01805557541933.034772219
2276214.29284325542063.904617086
#Sta/Elev= 30
       0 3900.13    38.5 3903.99    67.7 3900.93    92.7 3894.25   113.6 3893.14
   146.5 3895.77   171.9 3893.74   208.1  3887.1     222 3886.46  226.75  3887.1
     247 3892.16   259.5 3898.16     272 3906.76   292.9 3915.66   309.8  3914.5
     320 3908.44   340.5 3901.82   374.6 3902.97   380.7 3902.17   397.3 3896.38
   436.7 3896.22   454.1 3894.04     476 3894.69   489.9 3900.74   506.6 3912.27
   521.3 3924.62   529.3 3929.49   541.4 3932.68   602.8 3939.84     627 3946.26
#Mann= 4 ,-1,0
       0     .12       0   208.1    .045       0  226.75     .12       0
  433.11      .1       0
Bank Sta=208.1,226.75
XS Rating Curve= 0 ,0
Exp/Cntr(USF)=0,0
Exp/Cntr=0.3,0.1

Type RM Length L Ch R = 1 ,8951    ,150.8,149.9,149.5
XS GIS Cut Line= 2
2275603.56690054542134.7924497222276147.04028408542358.361768035
#Sta/Elev= 30
       0 3894.34     8.4 3894.44    20.7 3896.15    35.3 3895.08    57.5 3889.75
      85 3890.07   126.1 3887.23   137.1 3888.45   160.7 3888.63     165 3888.16
   173.7 3884.98     178  3884.4   221.2 3884.12   242.9 3882.51   268.6 3884.08
   289.63881.361   302.6  3880.7   307.7 3881.26   324.1  3890.5   353.2 3908.92
   359.7 3911.46     377 3911.93   389.9 3915.13   403.8 3917.12   415.9 3920.49
   437.5 3928.38   446.2 3929.53   454.8 3932.22   506.7 3938.21   587.7 3959.43
#Mann= 8 ,-1,0
       0     .12       0      40      .1       0     150     .12       0
     270      .1       0   289.6    .045       0   307.7      .1       0
     360     .12       0     470      .1       0
Bank Sta=289.6,307.7
XS Rating Curve= 0 ,0
Exp/Cntr(USF)=0,0
Exp/Cntr=0.3,0.1

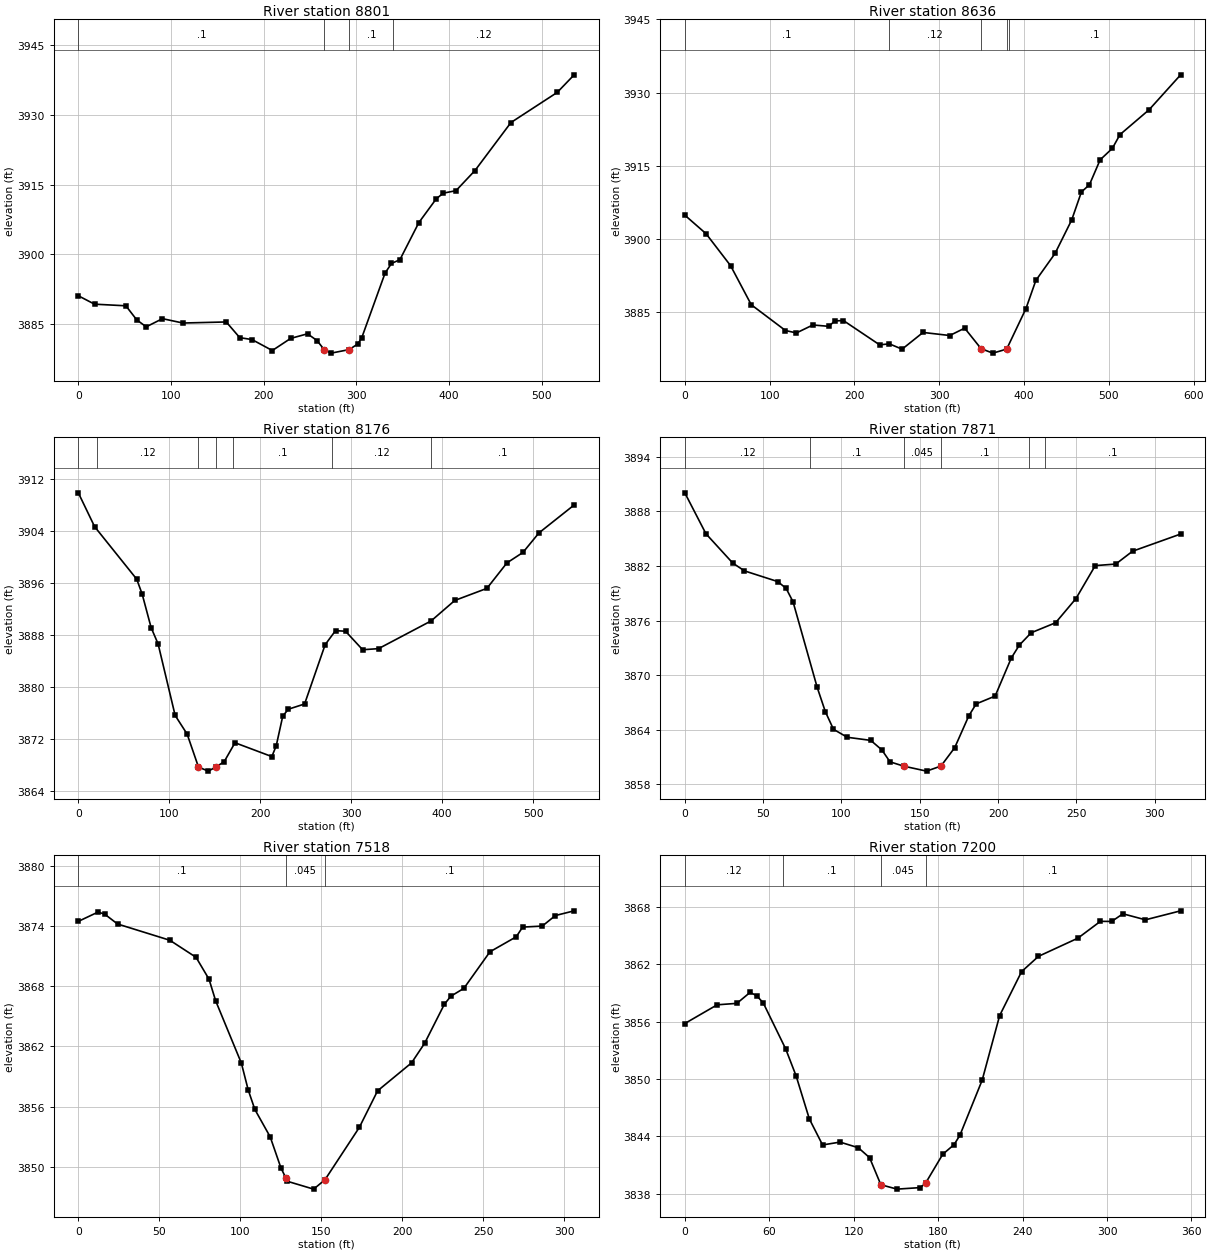
Type RM Length L Ch R = 1 ,8801    ,164.7,165.1,165.7
XS GIS Cut Line= 2
2275533.45331001542248.6775686142276020.83240691 542469.28073879
#Sta/Elev= 30
       0  3891.1    17.5 3889.29    51.3 3888.94    62.9 3885.94    73.2 3884.41
    90.8 3886.17   112.8 3885.23   159.6 3885.46   174.2 3882.08   187.4 3881.67
   209.3 3879.31   229.1 3881.92   247.3 3882.91   257.6 3881.45   265.4 3879.47
   272.8 3878.75   292.2 3879.51   301.7 3880.74   305.9 3882.11     331    3896
   337.9 3898.06     347 3898.87   367.4 3906.85   386.3    3912   393.8 3913.19
   407.5 3913.73     428 3918.07   466.8  3928.4   516.7 3934.88     535 3938.67
#Mann= 4 ,-1,0
       0      .1       0   265.4    .045       0   292.2      .1       0
     340     .12       0
Bank Sta=265.4,292.2
XS Rating Curve= 0 ,0
Exp/Cntr(USF)=0,0
Exp/Cntr=0.3,0.1

Type RM Length L Ch R = 1 ,8636    ,456.5,460.5,470.2
XS GIS Cut Line= 4
2275459.34689415542273.2439302982275551.06327113 542334.87573829
2275676.42031613542493.3270431692275921.65332904542611.013274096
#Sta/Elev= 30
       0 3904.89    25.1 3901.08      54 3894.53    78.4 3886.52   118.7 3881.24
   131.6 3880.75     151 3882.38   169.9  3882.1   176.8 3883.21     187 3883.29
   229.7 3878.31   241.2 3878.51   256.2 3877.42   280.9 3880.85   312.4 3880.22
     330 3881.73   349.33877.525   363.2 3876.61   379.53877.432   402.2 3885.72
   413.9 3891.51   436.5 3897.03   456.2 3903.92   467.6 3909.63   477.1 3911.13
   489.7 3916.23   504.1 3918.58   513.1  3921.4   547.4 3926.49   584.6 3933.65
#Mann= 5 ,-1,0
       0      .1       0   240.5     .12       0   349.3    .045       0
   379.5     .12       0  382.54      .1       0
Bank Sta=349.3,379.5
XS Rating Curve= 0 ,0
Exp/Cntr(USF)=0,0
Exp/Cntr=0.3,0.1

Type RM Length L Ch R = 1 ,8176    ,302.7,304.3,307.1
XS GIS Cut Line= 4
2275229.50794518542547.2723289182275381.58054629542640.746928088
2275453.89398394 542722.703895262275687.17819032542830.947318941
#Sta/Elev= 30
       0 3909.93    17.9 3904.72    64.2 3896.63    70.2 3894.32      80 3889.18
    87.7 3886.66   106.4 3875.66   119.6 3872.78  132.08  3867.7   142.9 3867.08
   151.6 3867.75   160.3 3868.53   172.2 3871.45   212.7 3869.32   217.5 3870.97
   224.7 3875.55   230.8 3876.61   248.7 3877.42   271.3 3886.55   282.7 3888.71
   293.7 3888.62   312.5 3885.77     330 3885.94   387.8 3890.21   413.8 3893.36
   449.1 3895.22   471.1 3899.14   488.7 3900.75   506.4 3903.77     545 3908.06
#Mann= 7 ,-1,0
       0      .1       0      20     .12       0  132.08    .045       0
   151.6     .12       0     170      .1       0   278.5     .12       0
   387.8      .1       0
Bank Sta=132.08,151.6
XS Rating Curve= 0 ,0
Exp/Cntr(USF)=0,0
Exp/Cntr=0.3,0.1

Type RM Length L Ch R = 1 ,7871    ,365.7,352.8,338.3
XS GIS Cut Line= 2
2275074.63461087 542783.68876385   2275320.01557542983.628804618
#Sta/Elev= 30
       0 3890.04    13.5 3885.54    30.6 3882.32    38.1 3881.46    59.4 3880.28
    64.7 3879.53    69.1 3878.06    84.5 3868.66    89.7 3865.99    94.9 3864.05
   103.7 3863.17   118.7 3862.83   125.8 3861.78     131 3860.47   139.7    3860
   154.3 3859.45   163.53860.004   172.3 3862.03   181.3 3865.53     186 3866.84
   198.1  3867.7   208.4 3871.88   213.5 3873.29   221.1 3874.66   236.7 3875.76
   249.7 3878.42     262 3882.04   275.1 3882.21   285.8 3883.62   316.5 3885.51
#Mann= 6 ,-1,0
       0     .12       0      80      .1       0   139.7    .045       0
   163.5      .1       0     220     .12       0     230      .1       0
Bank Sta=139.7,163.5
XS Rating Curve= 0 ,0
Exp/Cntr(USF)=0,0
Exp/Cntr=0.3,0.1

Type RM Length L Ch R = 1 ,7518    ,315.7,318.2,318.6
XS GIS Cut Line= 2
2274920.13548846 543198.109939262275223.68082308543158.121931107
#Sta/Elev= 30
       0 3874.46    12.1 3875.38    16.2 3875.19    24.2  3874.2    56.5 3872.58
    72.7 3870.88    80.7  3868.7    84.8 3866.55   100.7 3860.33   104.9 3857.67
     109 3855.73   118.5 3852.99   125.1 3849.91   128.1 3848.92   129.1 3848.57
   145.3 3847.79   152.3 3848.72   173.5 3853.93   184.8 3857.58   205.8 3860.37
   213.9 3862.33     226 3866.19     230    3867   238.1 3867.79   254.2 3871.43
   270.4 3872.92   274.4 3873.89   286.5 3873.99   294.6 3875.04   306.2 3875.51
#Mann= 3 ,-1,0
       0      .1       0   128.1    .045       0   152.3      .1       0
Bank Sta=128.1,152.3
XS Rating Curve= 0 ,0
Exp/Cntr(USF)=0,0
Exp/Cntr=0.3,0.1

Type RM Length L Ch R = 1 ,7200    ,126.2,128,129.9
XS GIS Cut Line= 3
2274892.54833353 543434.316084362274984.51053771543490.211689139
2275229.13373329543487.114180007
#Sta/Elev= 30
       0 3855.79      23 3857.75      37  3857.9    46.4 3859.05    51.1  3858.7
    55.7 3857.96    71.7 3853.13    79.1 3850.31    88.5 3845.81    97.9 3843.09
   110.3 3843.39   123.3  3842.8   131.3 3841.76   139.3 3838.93   150.8 3838.47
   167.3 3838.63   171.1  3839.1   183.3 3842.12   191.3 3843.12   195.4 3844.08
   211.3 3849.87   223.7 3856.62   239.3 3861.22   251.3 3862.82   279.3 3864.72
   295.3 3866.48   303.3 3866.47   311.3 3867.27   327.3 3866.64   352.3 3867.58
#Mann= 4 ,-1,0
       0     .12       0      70      .1       0   139.3    .045       0
   171.1      .1       0
Bank Sta=139.3,171.1
XS Rating Curve= 0 ,0
Exp/Cntr(USF)=0,0
Exp/Cntr=0.3,0.1

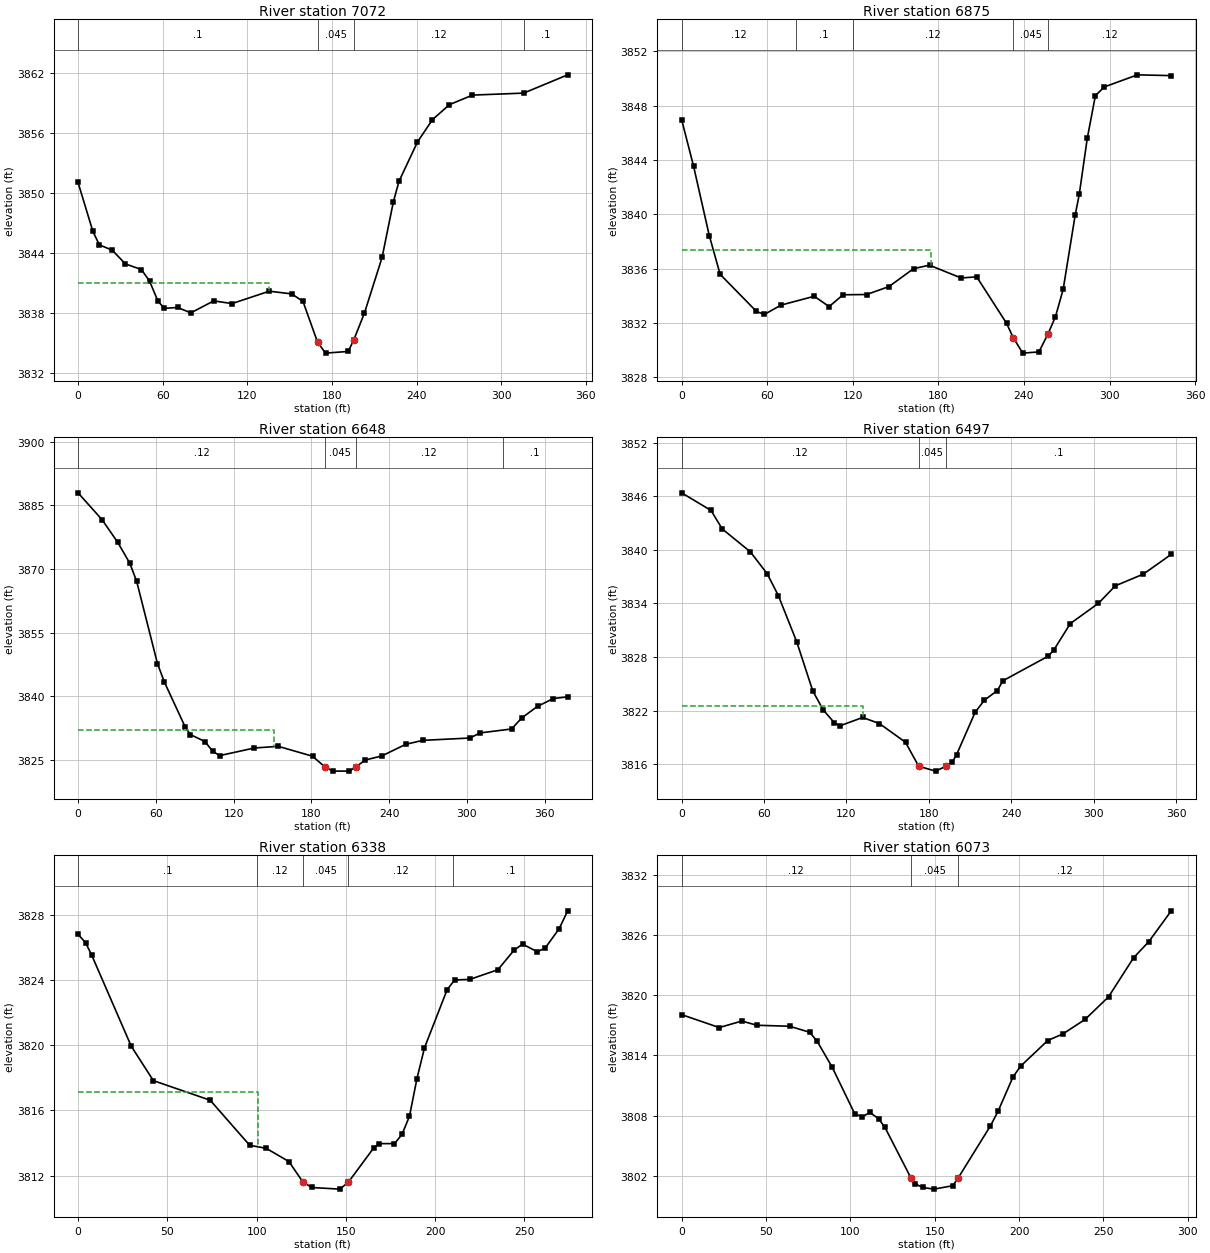
Type RM Length L Ch R = 1 ,7072    ,184.2,197.4,209.9
XS GIS Cut Line= 3
2274851.12257435543544.9349561592274969.11961886543613.339039934
2275179.46217647543627.019856689
#Sta/Elev= 30
       0 3851.08    10.5 3846.19    15.1 3844.83    24.3 3844.29    33.6 3842.92
    44.9 3842.36    50.7 3841.21    56.7 3839.18    61.3 3838.47    70.6 3838.56
      80 3838.02    96.2 3839.22   109.2 3838.95   135.6 3840.19   151.5 3839.92
   159.5 3839.17   169.8  3835.1   175.5 3833.99   191.6 3834.16   195.6 3835.34
   203.1 3838.01   215.6 3843.57   223.6 3849.14   227.6  3851.2   240.7 3855.13
   251.3 3857.36   263.3 3858.86   279.7 3859.82     316 3860.02   347.2 3861.85
#Mann= 4 ,-1,0
       0      .1       0   169.8    .045       0   195.6     .12       0
  316.39      .1       0
#XS Ineff= 2 , 0
          135.18 3841.05
Permanent Ineff=
       F       F
Bank Sta=169.8,195.6
XS Rating Curve= 0 ,0
Exp/Cntr(USF)=0,0
Exp/Cntr=0.3,0.1

Type RM Length L Ch R = 1 ,6875    ,219.5,227.3,235.7
XS GIS Cut Line= 2
  2274800.171464543627.0722085442275036.46423945543876.088441137
#Sta/Elev= 30
       0 3846.98     8.4 3843.54    19.4 3838.43      27 3835.58    52.5 3832.84
      58 3832.62    69.7 3833.31      93 3833.96   103.4  3833.2   113.2 3834.07
   129.7 3834.09   145.3 3834.67   162.7    3836   173.8 3836.25   195.9 3835.31
   206.9 3835.39   227.8 3831.97   232.5 3830.91   239.2 3829.77   250.5 3829.86
   256.73831.146   262.1 3832.45   267.5 3834.47   275.9 3839.93   278.8 3841.48
   284.4  3845.6   290.1 3848.75   296.4 3849.39   319.6 3850.28   343.3 3850.22
#Mann= 5 ,-1,0
       0     .12       0      80      .1       0     120     .12       0
   232.5    .045       0   256.7     .12       0
#XS Ineff= 2 , 0
          174.63 3837.37
Permanent Ineff=
       F       F
Bank Sta=232.5,256.7
XS Rating Curve= 0 ,0
Exp/Cntr(USF)=0,0
Exp/Cntr=0.3,0.1

Type RM Length L Ch R = 1 ,6648    ,178.8,150.5,132.1
XS GIS Cut Line= 4
2274626.30347927543712.8373341352274737.06181229543810.850044376
2274764.03874865543896.386671889 2274903.1844484543912.827287371
#Sta/Elev= 30
       0 3887.95    18.5 3881.64    30.7 3876.25    39.9 3871.38    45.2 3867.13
    61.3 3847.68    66.7  3843.3    82.6 3832.81    86.6 3830.99    97.9 3829.34
     104    3827   109.3 3826.03     136 3827.82   154.5 3828.21   180.9 3825.88
   190.5 3823.33   196.5 3822.38   209.1 3822.37   214.1  3823.3   221.6    3825
   234.2 3825.93   252.8 3828.69   265.9 3829.62   302.2 3830.17   310.2 3831.38
   334.4  3832.3   342.4 3834.94   354.5 3837.65   366.6 3839.47   377.7 3839.88
#Mann= 4 ,-1,0
       0     .12       0   190.5    .045       0   214.1     .12       0
  327.59      .1       0
#XS Ineff= 2 , 0
          151.21 3831.96
Permanent Ineff=
       F       F
Bank Sta=190.5,214.1
XS Rating Curve= 0 ,0
Exp/Cntr(USF)=0,0
Exp/Cntr=0.3,0.1

Type RM Length L Ch R = 1 ,6497    ,159.9,158.7,156.3
XS GIS Cut Line= 2
2274567.24562668544049.4150740022274916.10645394543975.880683944
#Sta/Elev= 30
       0 3846.39    21.4 3844.42    29.6 3842.34      50 3839.79    62.3 3837.33
    70.4 3834.89    83.8 3829.71    95.5  3824.2   103.1 3822.07   111.3 3820.62
   115.4  3820.3   131.8 3821.23     144 3820.55     163 3818.45   172.6 3815.77
   184.9 3815.22   192.5 3815.77   197.2 3816.26   200.2 3817.07   213.7 3821.81
   220.4 3823.16   229.9 3824.25   233.9 3825.34   266.7 3828.08   270.8 3828.74
     283 3831.75   303.5 3834.02   315.7 3835.97   336.2 3837.29   356.5  3839.5
#Mann= 3 ,-1,0
       0     .12       0   172.6    .045       0   192.5      .1       0
#XS Ineff= 2 , 0
          132.06 3822.56
Permanent Ineff=
       F       F
Bank Sta=172.6,192.5
XS Rating Curve= 0 ,0
Exp/Cntr(USF)=0,0
Exp/Cntr=0.3,0.1

Type RM Length L Ch R = 1 ,6338    ,252.1,265.4,279.9
XS GIS Cut Line= 2
2274660.21343546544206.8983267712274920.13548846544119.651763527
#Sta/Elev= 30
       0  3826.8     4.2 3826.29     7.6 3825.54    29.8 3819.94    42.2 3817.83
      74 3816.63    96.1 3813.87   105.4 3813.68   118.1 3812.87  125.763811.643
   130.8 3811.28   146.6 3811.18   151.43811.607   165.6 3813.71   168.7 3813.97
   177.2 3813.97   181.4 3814.53   185.6 3815.65   189.8 3817.96     194 3819.84
   206.7 3823.41   210.9    3824   219.5 3824.04   235.1 3824.63   244.2 3825.83
   248.9  3826.2   257.2 3825.73   261.6 3825.96   269.4 3827.14   274.2 3828.24
#Mann= 5 ,-1,0
       0      .1       0     100     .12       0  125.76    .045       0
   151.4     .12       0     210      .1       0
#XS Ineff= 2 , 0
          101.04 3817.16
Permanent Ineff=
       F       F
Bank Sta=125.76,151.4
XS Rating Curve= 0 ,0
Exp/Cntr(USF)=0,0
Exp/Cntr=0.3,0.1

Type RM Length L Ch R = 1 ,6073    ,257.1,269,277.1
XS GIS Cut Line= 2
2274580.23741916544328.6799879662274840.15947215544457.732196098
#Sta/Elev= 30
       0 3818.06    22.3 3816.77    35.7 3817.42    44.6    3817    64.1  3816.9
    75.9  3816.3    80.3 3815.41    89.2 3812.83   102.6 3808.17   107.1 3807.87
   111.6 3808.31   116.7 3807.68   120.5 3806.82     136 3801.74   138.4 3801.19
   142.8 3800.83   149.5 3800.66   160.7    3801  163.893801.774     183 3806.96
   187.5 3808.41   196.4 3811.85   200.9 3812.92     217 3815.48     226 3816.14
   239.1 3817.58     253 3819.83   267.9 3823.74   276.8 3825.32   290.2 3828.41
#Mann= 3 ,-1,0
       0     .12       0     136    .045       0  163.89     .12       0
Bank Sta=136,163.89
XS Rating Curve= 0 ,0
Exp/Cntr(USF)=0,0
Exp/Cntr=0.3,0.1