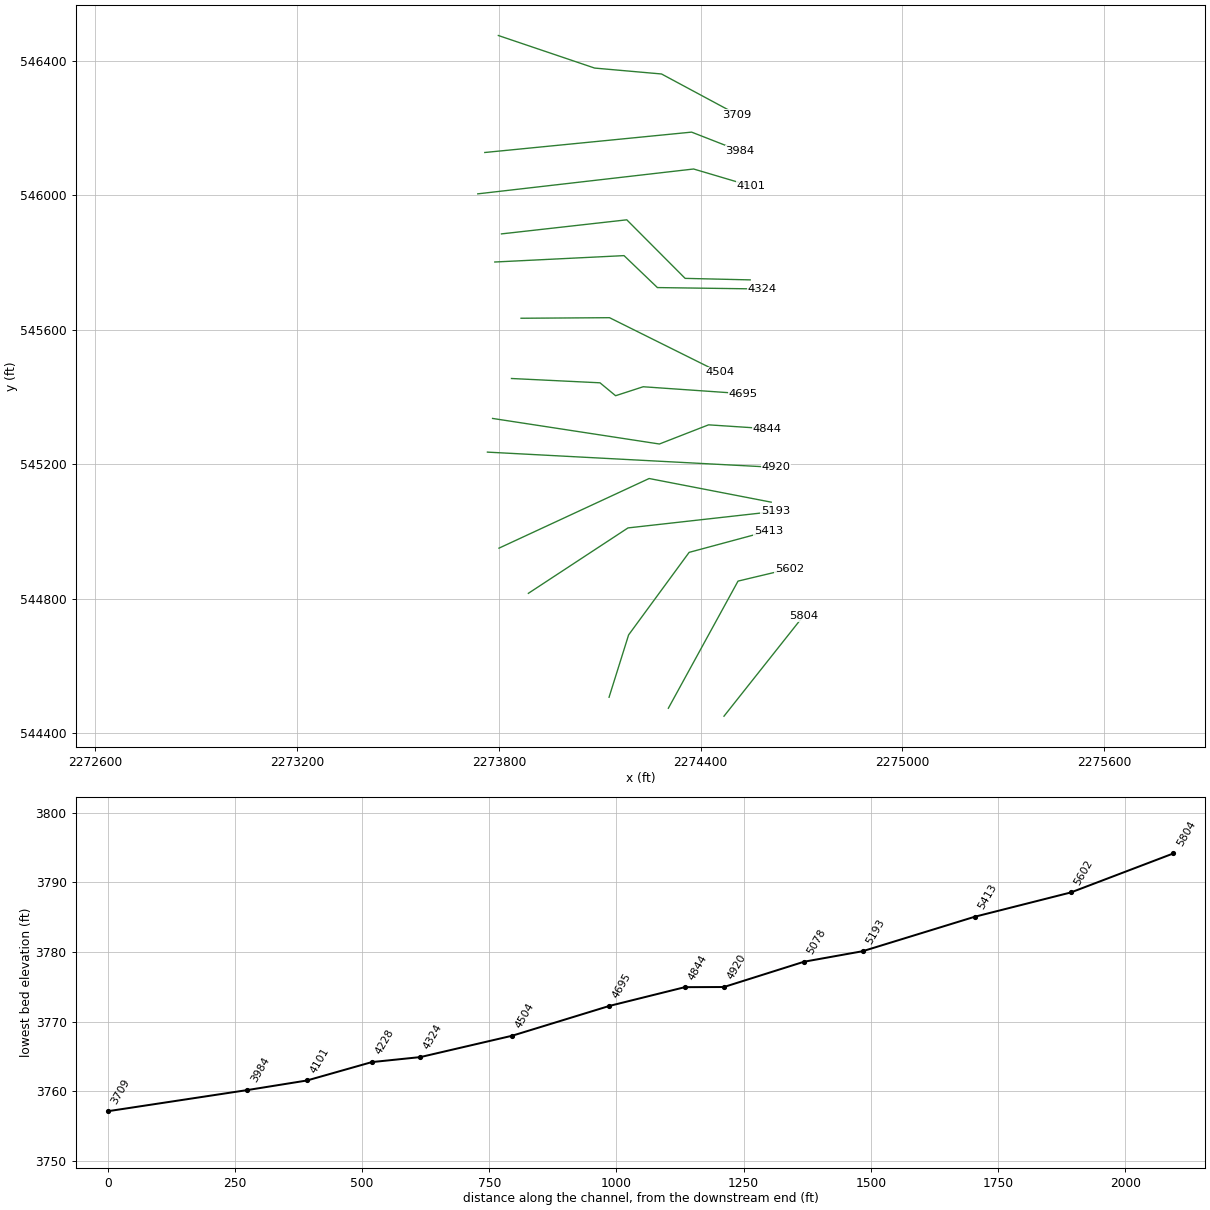
HEC-RAS study SECONDFK.prj: SECONDFK

--- SECONDFK.g01 (geometry) --- (continued)

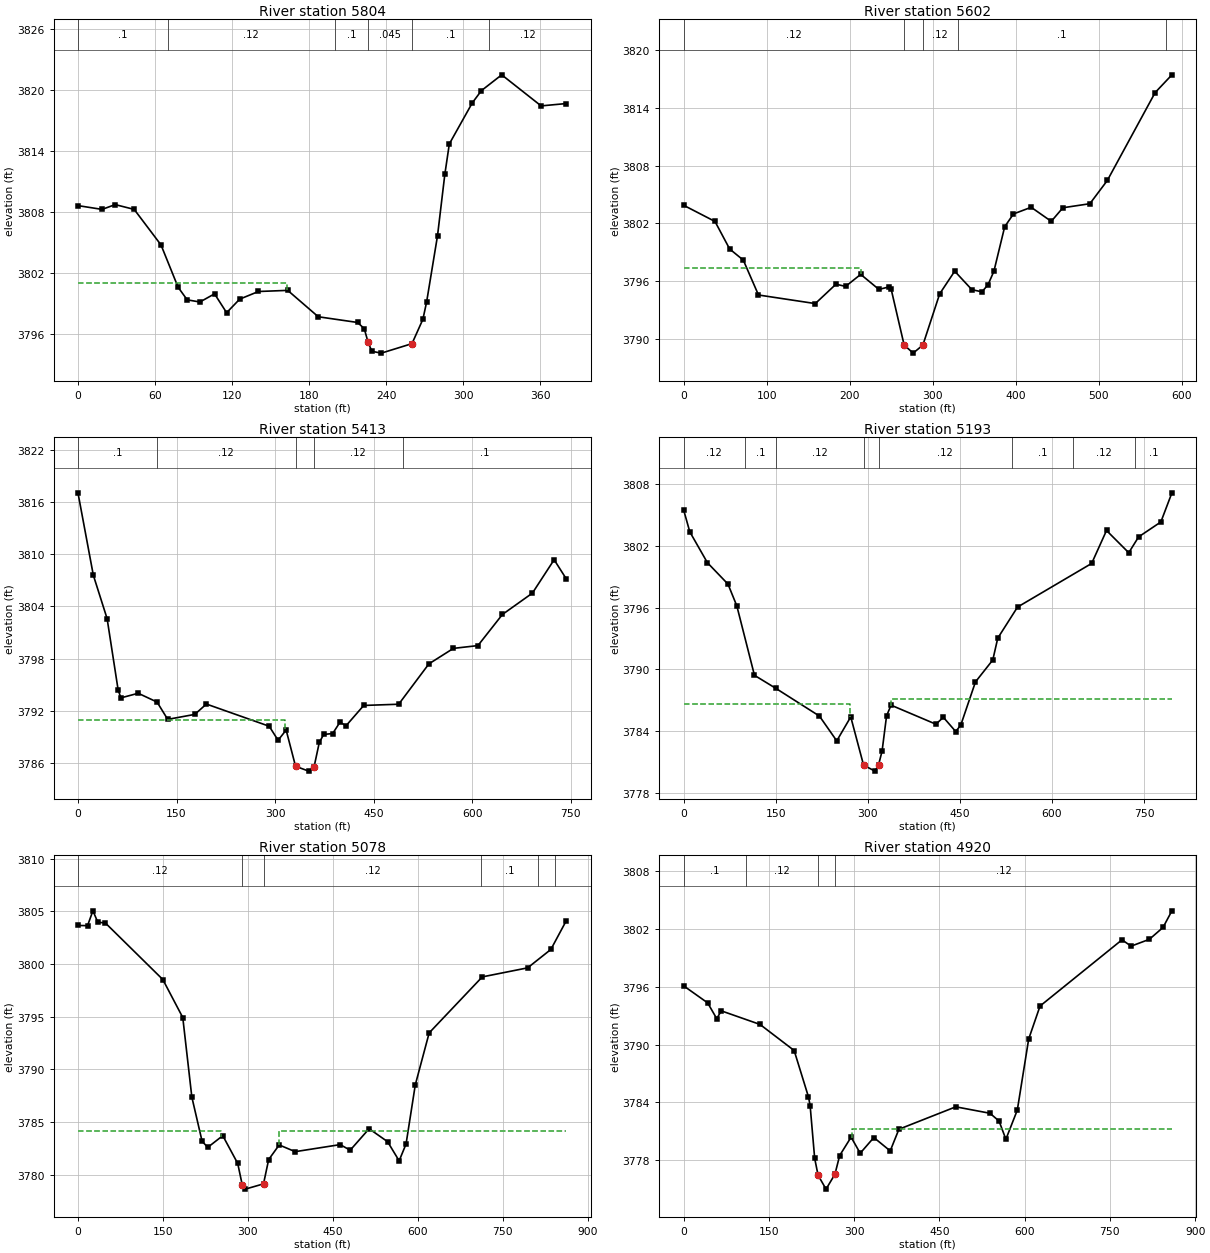
Type RM Length L Ch R = 1 ,5804    ,196.3,201.6,205.7
XS GIS Cut Line= 2
2274469.36157837544450.4616491612274705.65435382544748.554073579
#Sta/Elev= 30
       0 3808.63    18.8 3808.26      29 3808.73    43.8 3808.26    64.7 3804.77
      78 3800.62    85.1 3799.38      95 3799.17   106.4 3799.97   115.8 3798.12
     126 3799.45   140.6  3800.2   163.4 3800.31   187.2 3797.72   217.8 3797.16
     223 3796.56     226 3795.22   228.9 3794.33   236.3 3794.15   260.2 3795.08
   268.7 3797.47   271.6 3799.17   280.1 3805.68   285.8 3811.71   289.3 3814.69
   307.2 3818.72   314.3 3819.92   330.1 3821.47   360.8 3818.42   380.4 3818.65
#Mann= 6 ,-1,0
       0      .1       0      70     .12       0     200      .1       0
     226    .045       0   260.2      .1       0     320     .12       0
#XS Ineff= 2 , 0
          163.12 3801.05
Permanent Ineff=
       F       F
Bank Sta=226,260.2
XS Rating Curve= 0 ,0
Exp/Cntr(USF)=0,0
Exp/Cntr=0.3,0.1

Type RM Length L Ch R = 1 ,5602    ,191.5,189.1,186.7
XS GIS Cut Line= 3
2274303.95663555544474.0909267072274511.16722326544852.159367431
2274663.84870893544888.512102116
#Sta/Elev= 30
       0 3803.89    37.8 3802.21    55.5 3799.35    71.9  3798.2    90.2 3794.58
   158.6 3793.69   183.5  3795.7   195.1 3795.47   213.3 3796.72   235.2 3795.16
     247 3795.41   249.8 3795.25   265.63789.392   276.5 3788.55   288.2 3789.39
   308.4  3794.7   326.5 3797.05   347.2 3795.13   359.3 3794.91   366.6 3795.64
   373.7 3797.04   386.7 3801.66   397.3 3802.99   418.6 3803.68   442.8 3802.22
   456.8 3803.63   489.3 3804.05   510.3 3806.46   567.9 3815.58   588.1 3817.42
#Mann= 5 ,-1,0
       0     .12       0   265.6    .045       0   288.2     .12       0
     330      .1       0  581.13     .12       0
#XS Ineff= 2 , 0
          213.36 3797.42
Permanent Ineff=
       F       F
Bank Sta=265.6,288.2
XS Rating Curve= 0 ,0
Exp/Cntr(USF)=0,0
Exp/Cntr=0.3,0.1

Type RM Length L Ch R = 1 ,5413    ,226.3,220.1,213
XS GIS Cut Line= 4
2274127.64587233544506.8083879232274185.81024782544692.207334817
2274365.75628451544937.5882939412274602.04905997 545001.20557964
#Sta/Elev= 30
       0 3817.05    23.4 3807.58    44.4 3802.58    61.2 3794.37    65.4 3793.48
    91.7 3794.01   120.4    3793   136.6 3791.01   177.8 3791.58   195.5 3792.77
   291.1 3790.22   304.6 3788.61   316.9 3789.78   331.2 3785.62   351.2 3785.06
   359.2 3785.48   367.4 3788.37   374.1 3789.28   387.7 3789.38   398.9 3790.69
     408 3790.27     435 3792.61   488.2 3792.75   534.2 3797.39   571.5 3799.17
   608.8 3799.49   646.1 3803.07   691.7 3805.52   724.8 3809.36   743.3 3807.16
#Mann= 5 ,-1,0
       0      .1       0     120     .12       0   331.2    .045       0
   359.2     .12       0  494.31      .1       0
#XS Ineff= 2 , 0
          315.66 3790.97
Permanent Ineff=
       F       F
Bank Sta=331.2,359.2
XS Rating Curve= 0 ,0
Exp/Cntr(USF)=0,0
Exp/Cntr=0.3,0.1

Type RM Length L Ch R = 1 ,5193    ,118.8,115.3,111.9
XS GIS Cut Line= 3
2273887.71782341544815.8066327462274183.99261109545010.293763312
2274622.04306404545059.369955136
#Sta/Elev= 30
       0 3805.51    10.1 3803.37    38.8 3800.37    72.3 3798.29    86.7 3796.17
   115.4 3789.43     150 3788.17   221.2 3785.47   249.4 3783.06   272.2 3785.39
   293.1  3780.7   311.6 3780.12   317.43780.714   323.2 3782.06   330.5 3785.48
   337.8 3786.53   410.9 3784.68     423 3785.35   443.1 3783.97   451.3 3784.58
   475.3 3788.79   503.5 3790.92   511.6 3793.04   543.8 3796.06   664.5  3800.3
   688.7  3803.5   724.9 3801.34     741 3802.88   777.2 3804.33   795.2 3807.16
#Mann= 8 ,-1,0
       0     .12       0     100      .1       0     150     .12       0
   293.1    .045       0   317.4     .12       0  534.41      .1       0
  634.41     .12       0  734.41      .1       0
#XS Ineff= 2 , 0
          271.68 3786.62  337.37         3787.11
Permanent Ineff=
       F       F
Bank Sta=293.1,317.4
XS Rating Curve= 0 ,0
Exp/Cntr(USF)=0,0
Exp/Cntr=0.3,0.1

Type RM Length L Ch R = 1 ,5078    ,167.6,157.6,148.4
XS GIS Cut Line= 3
2273800.32485461544950.0875060062274246.85151259545157.199870771
2274609.77317929545086.895673557
#Sta/Elev= 30
       0 3803.67    16.9 3803.65    26.4 3805.06    35.1 3803.97    48.3 3803.91
   149.8 3798.53     185 3794.92     201 3787.36   219.1 3783.16   229.1 3782.58
   255.6 3783.69     282 3781.05  289.88 3779.03   295.3 3778.61   327.5 3779.11
   336.6 3781.42   355.2 3782.81   383.4 3782.17   462.8 3782.84   480.5 3782.31
   513.9 3784.35   546.5 3783.12   566.9  3781.3   579.1  3782.9   595.4 3788.52
   619.9 3793.46   713.6 3798.78   793.7 3799.64   834.7 3801.39   861.9 3804.12
#Mann= 6 ,-1,0
       0     .12       0  289.88    .045       0   327.5     .12       0
  712.22      .1       0  812.22     .12       0  842.22      .1       0
#XS Ineff= 2 , 0
          252.61 3784.15  354.91         3784.09
Permanent Ineff=
       F       F
Bank Sta=289.88,327.5
XS Rating Curve= 0 ,0
Exp/Cntr(USF)=0,0
Exp/Cntr=0.3,0.1

Type RM Length L Ch R = 1 ,4920    ,78.7,76.7,75.1
XS GIS Cut Line= 2
2273765.93616221545235.6807183592274623.86070078545190.239800003
#Sta/Elev= 30
       0  3796.1    42.3 3794.33    58.3 3792.69    66.3  3793.5   134.4 3792.09
   194.5 3789.38   219.7 3784.56   222.6 3783.66   230.6 3778.18   236.6 3776.42
   250.6 3774.98   266.2 3776.52   274.6 3778.47   294.7 3780.38   310.7 3778.71
   334.7 3780.34   363.5 3778.95   378.8  3781.2   478.9 3783.53     539 3782.86
     555 3782.05     567 3780.16   587.1 3783.19   607.1 3790.57   627.1    3794
   771.3 3800.88   787.3 3800.22   819.4 3800.93   843.4 3802.16   859.1 3803.89
#Mann= 4 ,-1,0
       0      .1       0     110     .12       0   236.6    .045       0
   266.2     .12       0
#XS Ineff= 2 , 0
                          295.76         3781.26
Permanent Ineff=
       F       F
Bank Sta=236.6,266.2
XS Rating Curve= 0 ,0
Exp/Cntr(USF)=0,0
Exp/Cntr=0.3,0.1

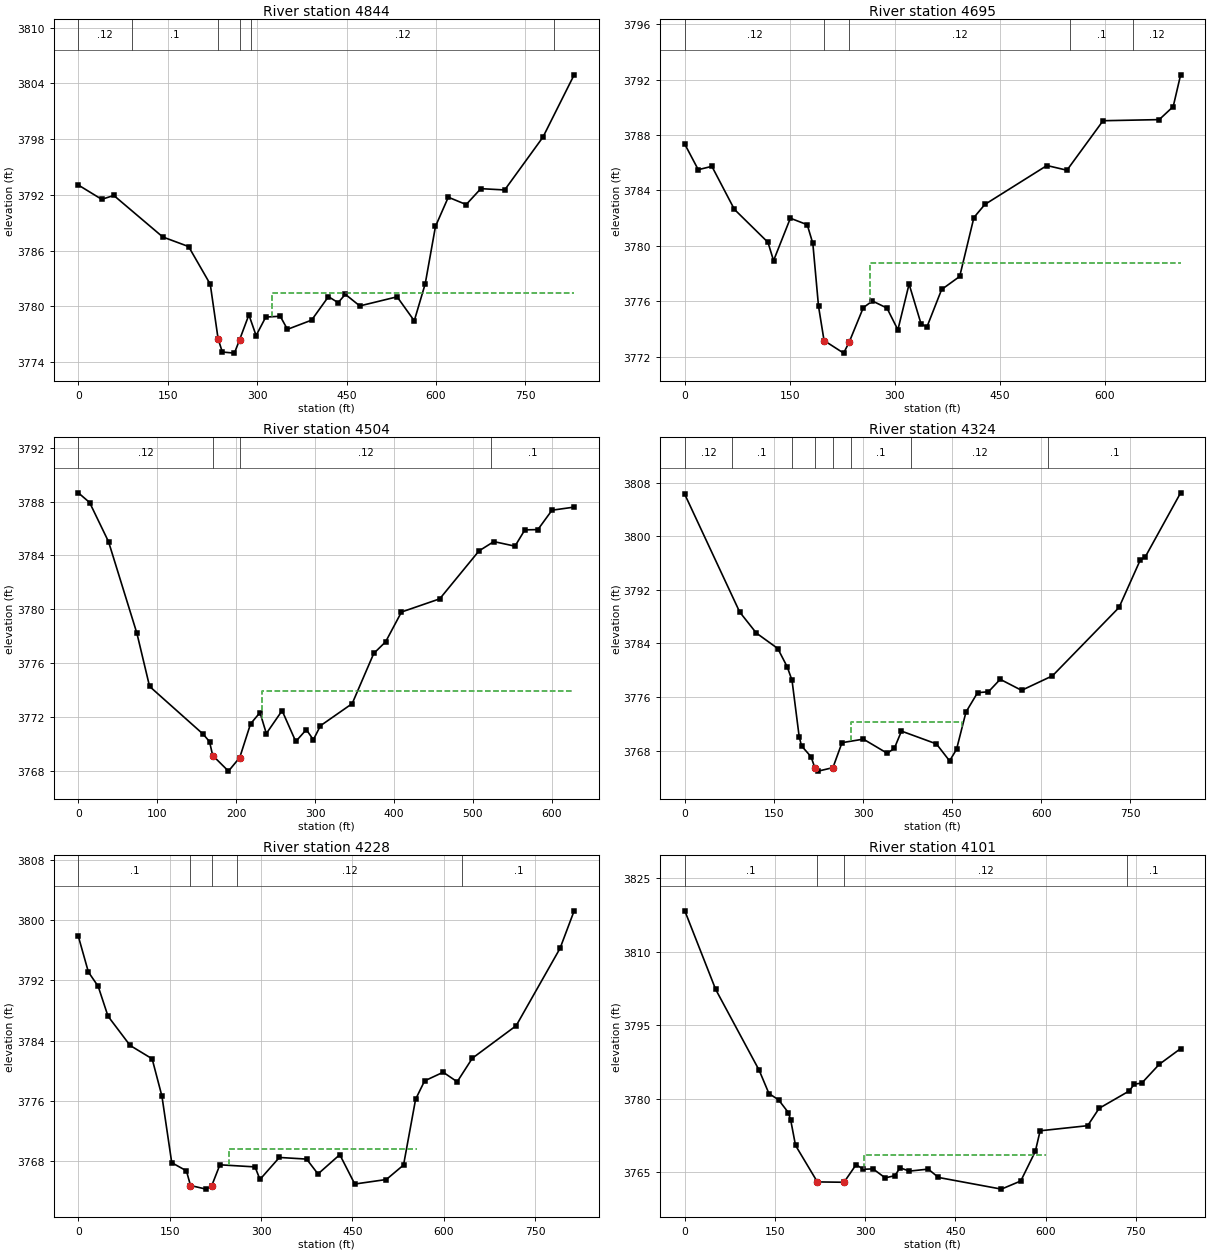
Type RM Length L Ch R = 1 ,4844    ,146.1,148.3,150.9
XS GIS Cut Line= 4
2273781.32372023545335.810533963 2274277.2533276545259.805996434
2274423.56206235545316.8093995812274596.47238522545305.408718952
#Sta/Elev= 30
       0 3793.05    39.3 3791.51    59.5 3791.93   141.7 3787.46     185 3786.43
   221.4 3782.37   234.53776.511   241.6 3775.08   261.9 3774.96   270.53776.381
   286.2 3779.08   298.3 3776.85   314.5 3778.84   338.8 3778.93   350.9 3777.52
   391.4 3778.51   419.7 3781.04   435.9 3780.39     448 3781.29   472.3 3780.04
   534.9 3781.02   563.7 3778.44   582.1 3782.43   599.3  3788.6   620.8 3791.74
   650.8 3790.95   675.4 3792.66   715.4 3792.52   779.6  3798.2     832 3804.91
#Mann= 6 ,-1,0
       0     .12       0      90      .1       0   234.5    .045       0
   270.5      .1       0     290     .12       0  798.74      .1       0
#XS Ineff= 2 , 0
                          324.29         3781.42
Permanent Ineff=
       F       F
Bank Sta=234.5,270.5
XS Rating Curve= 0 ,0
Exp/Cntr(USF)=0,0
Exp/Cntr=0.3,0.1

Type RM Length L Ch R = 1 ,4695    ,190.1,191.3,192.6
XS GIS Cut Line= 5
2273837.50815506545454.5885228782274100.70542484545441.767451813
 2274147.0728567545403.3944047622274229.14854066545430.042354103
 2274526.7742351545409.366364296
#Sta/Elev= 30
       0 3787.34    19.2  3785.5    38.7 3785.74    70.8 3782.64   118.8 3780.26
   126.8 3778.94   150.8    3782   174.9 3781.53   182.9 3780.18     191 3775.66
   198.9 3773.18   226.9 3772.27   234.9 3773.07     255 3775.55     268 3776.03
   288.8 3775.52   304.4 3773.95   320.4 3777.25   337.5 3774.38   345.9 3774.16
   366.9 3776.86   392.7  3777.8     413 3782.05   428.6 3782.99   517.3  3785.8
   545.9 3785.46   597.5 3789.03   677.7 3789.11   697.7 3790.05   708.3 3792.34
#Mann= 5 ,-1,0
       0     .12       0   198.9    .045       0   234.9     .12       0
  549.99      .1       0  639.99     .12       0
#XS Ineff= 2 , 0
                          264.42         3778.79
Permanent Ineff=
       F       F
Bank Sta=198.9,234.9
XS Rating Curve= 0 ,0
Exp/Cntr(USF)=0,0
Exp/Cntr=0.3,0.1

Type RM Length L Ch R = 1 ,4504    ,179.3,180.2,181.7
XS GIS Cut Line= 3
2273865.90618259545633.7431631612274129.01626146545635.399306794
2274456.13733052545472.694109705
#Sta/Elev= 30
       0 3788.65    14.3 3787.93    38.3 3785.02    74.3 3778.21    90.3 3774.28
   158.3 3770.73   166.3 3770.18   170.3 3769.15   190.3 3767.99   204.63768.998
   218.3  3771.5   230.3 3772.34   238.3 3770.78   258.3 3772.48   275.6 3770.19
     289 3771.07   297.9 3770.32   306.9 3771.36   347.1    3773   374.5 3776.73
   389.5 3777.59   409.6  3779.8   458.1 3780.78   507.9 3784.34   526.7 3785.03
   553.5 3784.69     566  3785.9   582.5 3785.92   600.4 3787.36   628.5 3787.59
#Mann= 4 ,-1,0
       0     .12       0   170.3    .045       0   204.6     .12       0
  523.12      .1       0
#XS Ineff= 2 , 0
                          232.84         3773.94
Permanent Ineff=
       F       F
Bank Sta=170.3,204.6
XS Rating Curve= 0 ,0
Exp/Cntr(USF)=0,0
Exp/Cntr=0.3,0.1

Type RM Length L Ch R = 1 ,4324    ,94.4,95.5,96.8
XS GIS Cut Line= 4
2273787.91065435545800.9583653812274172.15581629545819.959499763
2274271.38396251545724.9538278522274583.84706124545720.731353545
#Sta/Elev= 30
       0 3806.28    92.4  3788.7   120.4 3785.56   156.5 3783.25   172.5 3780.49
   180.5 3778.49   192.5 3770.09   196.5  3768.7   212.5 3767.08   219.1 3765.38
   224.5 3764.93  249.34 3765.45   264.6 3769.18   300.6 3769.71   340.7  3767.6
   352.7 3768.33   364.7 3770.91   423.5    3769   445.7 3766.46   457.4 3768.18
   473.3 3773.76   492.8 3776.65   511.2 3776.79   530.9 3778.65   566.9    3777
   618.9 3779.17   730.9 3789.38   766.4 3796.42   775.3 3796.97   834.6 3806.51
#Mann= 8 ,-1,0
       0     .12       0      80      .1       0     180     .12       0
   219.1    .045       0  249.34     .12       0     280      .1       0
     380     .12       0  612.09      .1       0
#XS Ineff= 1 ,-1
  280.45  466.193772.302
Permanent Ineff=
       F
Bank Sta=219.1,249.34
XS Rating Curve= 0 ,0
Exp/Cntr(USF)=0,0
Exp/Cntr=0.3,0.1

Type RM Length L Ch R = 1 ,4228    ,128.5,127.6,127.4
XS GIS Cut Line= 4
 2273807.7418071545884.5770324882274180.33710073545926.429030766
2274353.84485977545752.3290950742274547.33110581545747.816394159
#Sta/Elev= 30
       0 3797.89    16.5 3793.13    32.6 3791.22    48.7 3787.25      85 3783.35
   121.2 3781.57   137.3 3776.59   153.4 3767.73   177.5 3766.65   184.23764.693
   209.7 3764.21     2193764.646   232.5 3767.45   290.2 3767.17   298.3  3765.5
   330.2 3768.43   374.9 3768.21   393.6 3766.23   429.4  3768.8     454 3764.89
   505.8 3765.49   534.1 3767.42   553.9 3776.18   568.7 3778.63   599.2 3779.78
   622.2 3778.51   647.1 3781.65   719.1 3785.98   791.1 3796.28   814.3 3801.28
#Mann= 5 ,-1,0
       0      .1       0   184.2    .045       0     219      .1       0
     260     .12       0  630.73      .1       0
#XS Ineff= 1 ,-1
  247.89  556.883769.525
Permanent Ineff=
       F
Bank Sta=184.2,219
XS Rating Curve= 0 ,0
Exp/Cntr(USF)=0,0
Exp/Cntr=0.3,0.1

Type RM Length L Ch R = 1 ,4101    ,119,116.9,117.9
XS GIS Cut Line= 3
2273737.24096266546003.6371321242274379.05705734546077.530432499
2274550.06726678546026.860740813
#Sta/Elev= 30
       0 3818.29    51.3 3802.28   123.7 3785.78   139.9 3781.05     156 3779.76
   172.1 3777.18   176.1 3775.64   184.1 3770.48   220.4 3763.04   264.7 3762.97
   284.8 3766.55   296.9 3765.61     313  3765.7   333.1 3763.87   349.2  3764.3
   357.9 3765.92   373.4 3765.24   404.8 3765.65   421.7 3763.95   526.4 3761.57
   558.6 3763.23   582.8 3769.26   590.8 3773.46   669.8  3774.5   688.9 3778.04
     739 3781.58   747.3 3782.96   759.8 3783.18   788.8    3787   824.4 3790.21
#Mann= 4 ,-1,0
       0      .1       0   220.4    .045       0   264.7     .12       0
  736.06      .1       0
#XS Ineff= 1 ,-1
  297.84  600.213768.602
Permanent Ineff=
       F
Bank Sta=220.4,264.7
XS Rating Curve= 0 ,0
Exp/Cntr(USF)=0,0
Exp/Cntr=0.3,0.1

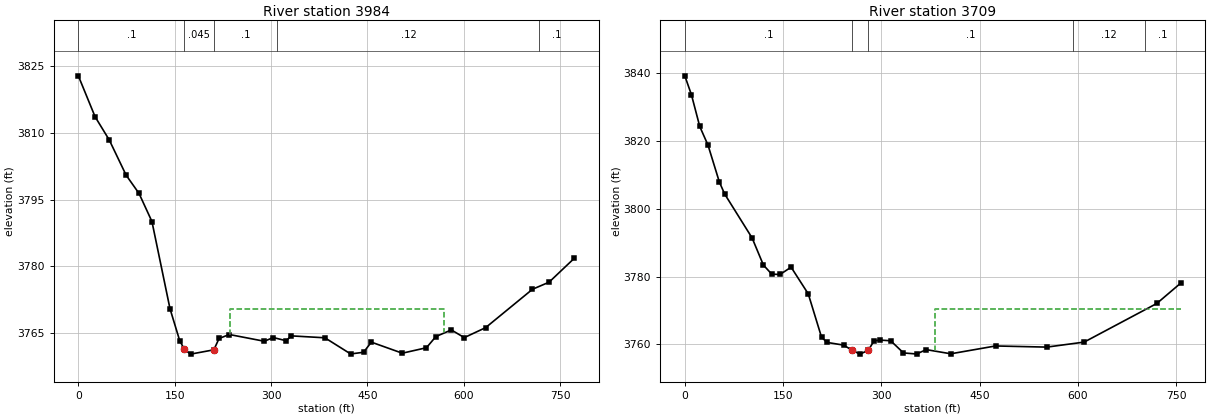
Type RM Length L Ch R = 1 ,3984    ,293.8,274.6,267.8
XS GIS Cut Line= 3
2273758.17193616 546126.614437622274373.02683145546187.202328761
2274516.64257342546131.102429556
#Sta/Elev= 30
       0 3822.88    26.1 3813.66    48.1 3808.45    74.4 3800.51    94.5 3796.39
   114.6 3790.07   142.7 3770.44   157.8 3763.25   165.2 3761.26   174.8  3760.2
     211 3761.17   219.1 3763.72   235.1 3764.62   289.6  3763.1   303.5 3763.94
   323.6 3763.21   331.6 3764.31   383.9 3763.88     424 3760.24   444.1 3760.62
   456.2  3762.9   504.4 3760.41     542 3761.64   556.7 3764.16   580.8 3765.65
   600.9 3763.92   634.1 3766.16   707.1 3774.81   732.9  3776.4     772 3781.76
#Mann= 5 ,-1,0
       0      .1       0   165.2    .045       0     211      .1       0
     310     .12       0  717.83      .1       0
#XS Ineff= 1 ,-1
  236.05  569.993770.443
Permanent Ineff=
       F
Bank Sta=165.2,211
XS Rating Curve= 0 ,0
Exp/Cntr(USF)=0,0
Exp/Cntr=0.3,0.1

Type RM Length L Ch R = 1 ,3709    ,235.5,226.4,220.7
XS GIS Cut Line= 4
2273798.56386359546474.4338126932274084.79782342546377.624857746
2274283.65220533546360.0788828712274508.12333153546239.515163969
#Sta/Elev= 30
       0 3839.25    10.1  3833.7    22.8 3824.32    35.5 3818.76    52.7 3807.95
    60.8  3804.4   102.7 3791.43   119.9 3783.45   132.6 3780.76   145.3 3780.65
   162.2 3782.81   188.4 3774.93   208.6 3762.19   216.8 3760.62   242.4 3759.82
   255.8 3758.25   267.3 3757.16   279.9 3758.28   288.8 3761.06   297.3 3761.31
   314.2  3761.1   333.7 3757.51   353.7  3757.2   368.4 3758.49   405.9 3757.26
   474.2 3759.57   552.3 3759.23   609.4 3760.71   720.3 3772.11   756.6 3778.08
#Mann= 5 ,-1,0
       0      .1       0   255.8    .045       0   279.9      .1       0
  591.79     .12       0  701.79      .1       0
#XS Ineff= 2 , 0
                          382.32         3770.43
Permanent Ineff=
       F       F
Bank Sta=255.8,279.9
XS Rating Curve= 0 ,0
Exp/Cntr(USF)=0,0
Exp/Cntr=0.3,0.1