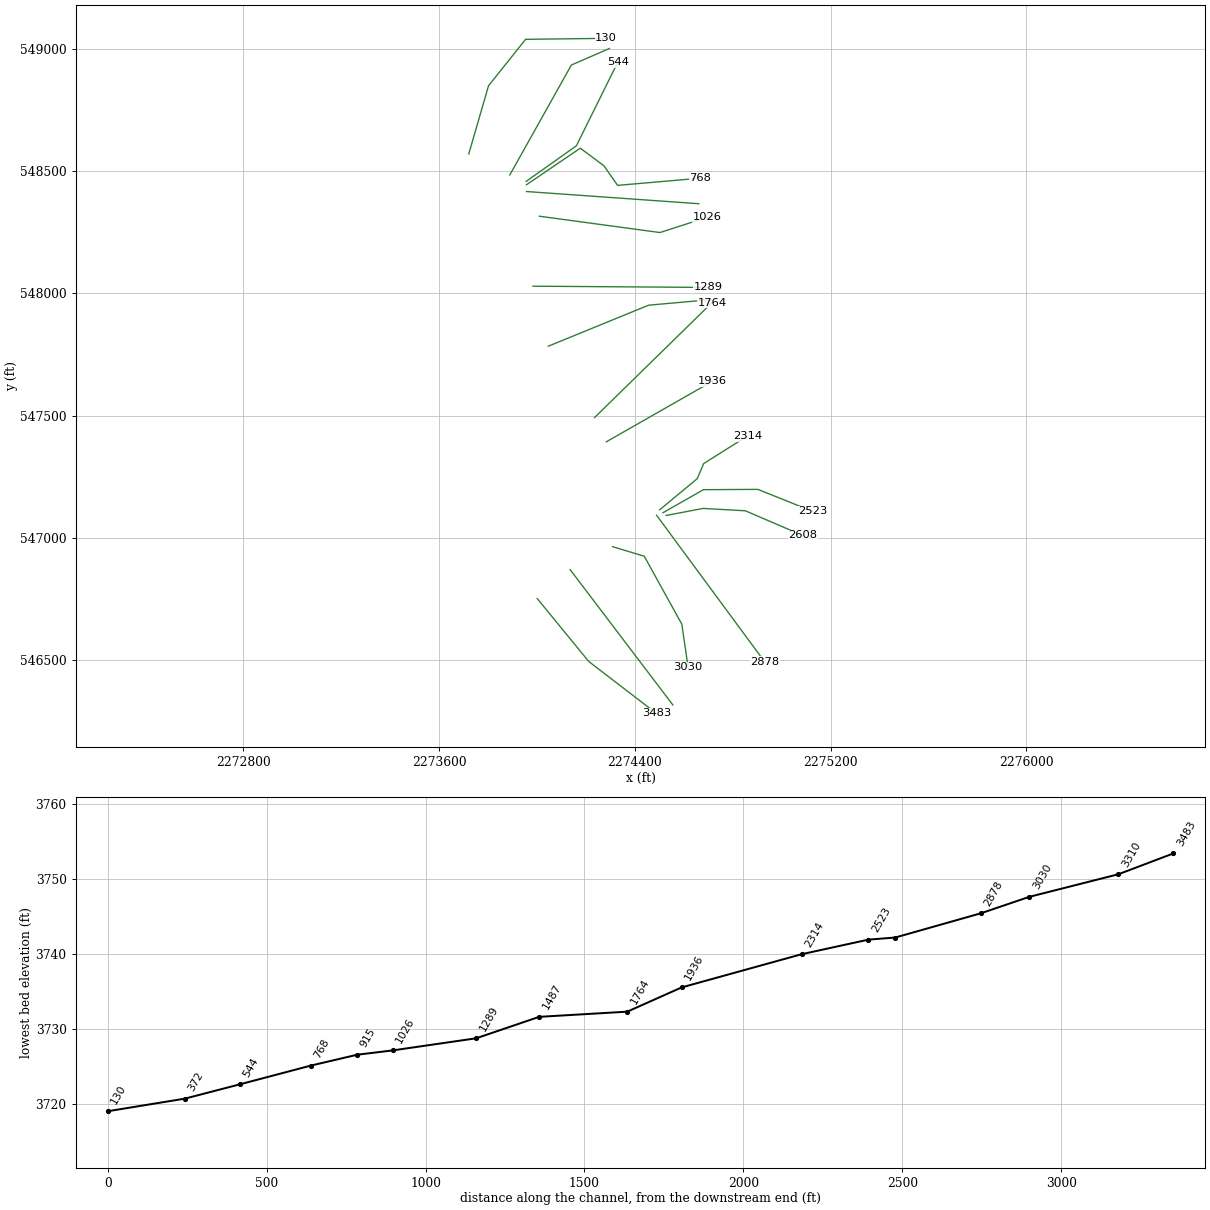
HEC-RAS study SECONDFK.prj: SECONDFK

--- SECONDFK.g01 (geometry) --- (continued)

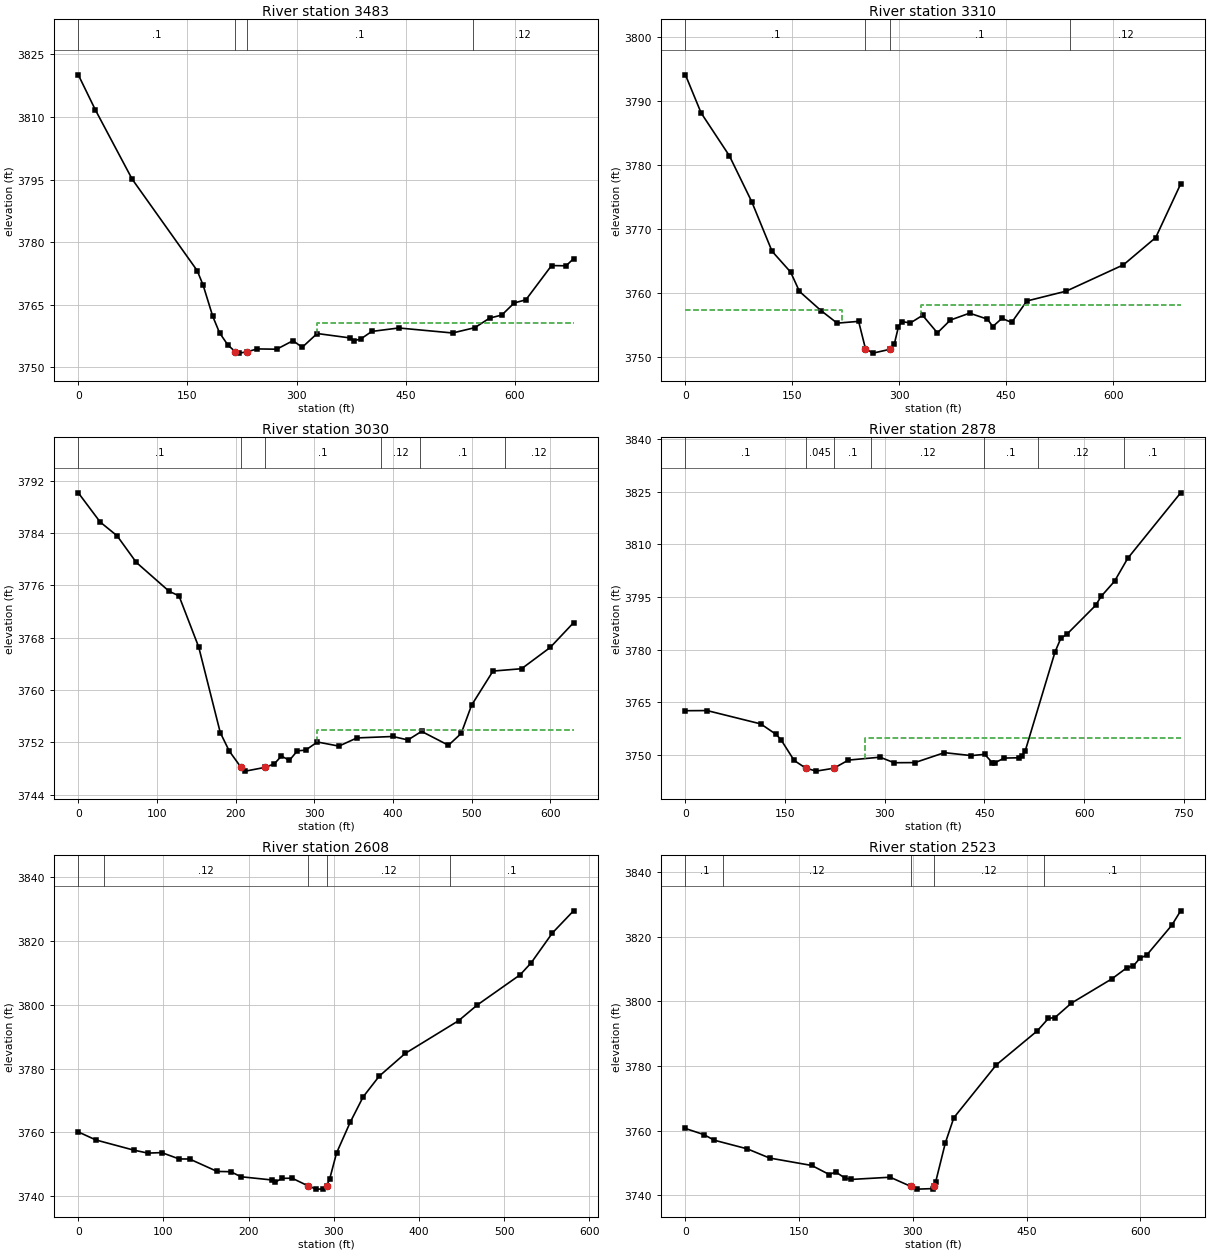
Type RM Length L Ch R = 1 ,3483    ,172.6,173.2,175.4
XS GIS Cut Line= 3
2274001.28930533546752.2055122642274211.59340409546495.167169335
2274488.10434876  546282.9158104
#Sta/Elev= 30
       0 3820.12    23.5  3811.7      74 3795.12   163.4 3773.19   171.6 3769.69
   184.8 3762.23   194.1  3758.3   205.5 3755.37   215.8 3753.74     221 3753.41
     232 3753.72   245.8 3754.42   272.7 3754.35   295.1 3756.39   307.8 3754.81
   328.3 3758.11   373.2 3757.06   379.6 3756.43   388.1 3756.78   403.4 3758.61
   440.5 3759.44   514.4 3758.24     545 3759.51   565.3  3761.8   582.1 3762.54
   599.2 3765.44   615.2 3766.19   650.5  3774.4   670.4 3774.34   680.7 3776.04
#Mann= 4 ,-1,0
       0      .1       0   215.8    .045       0     232      .1       0
  542.11     .12       0
#XS Ineff= 2 , 0
                          327.67         3760.55
Permanent Ineff=
       F       F
Bank Sta=215.8,232
XS Rating Curve= 0 ,0
Exp/Cntr(USF)=0,0
Exp/Cntr=0.3,0.1

Type RM Length L Ch R = 1 ,3310    ,275.7,280.2,270.4
XS GIS Cut Line= 2
2274135.42613571546870.7250397722274555.50218096 546317.35563401
#Sta/Elev= 30
       0 3794.08      22 3788.13    61.6 3781.45      93 3774.28   121.5 3766.54
   147.6 3763.28     160 3760.26   190.1 3757.28   212.9 3755.31     243 3755.59
   252.6 3751.31   263.1 3750.63   286.43751.213   293.2 3752.11   298.9 3754.77
   303.3 3755.55   315.7 3755.35   332.8 3756.53   353.5 3753.79   371.7 3755.79
   398.7 3756.87   423.8 3755.93   431.2 3754.78   444.1 3756.06   457.7 3755.42
     479 3758.77   534.3 3760.31   614.6 3764.42   659.8 3768.67   694.8 3777.04
#Mann= 4 ,-1,0
       0      .1       0   252.6    .045       0   286.4      .1       0
     540     .12       0
#XS Ineff= 2 , 0
          220.18 3757.33  330.27         3758.08
Permanent Ineff=
       F       F
Bank Sta=252.6,286.4
XS Rating Curve= 0 ,0
Exp/Cntr(USF)=0,0
Exp/Cntr=0.3,0.1

Type RM Length L Ch R = 1 ,3030    ,149.4,152,155.2
XS GIS Cut Line= 4
2274309.57973687546964.0394903832274438.64165006546925.205490285
2274592.16893021 546647.394221442274617.82427528546471.835008071
#Sta/Elev= 30
       0 3790.12    27.8 3785.66    49.3 3783.56    73.7  3779.5   115.5 3775.08
     128 3774.39   153.1 3766.56   180.5  3753.5   191.9 3750.69   206.6 3748.24
   212.5 3747.62   237.2 3748.19   249.1 3748.72   258.2 3749.92   268.4 3749.27
   278.5 3750.72     289 3750.82   303.9 3752.07   331.3 3751.44   354.2 3752.69
   399.9 3752.91   419.1 3752.38   436.4 3753.69   470.6 3751.57   486.8 3753.38
     500 3757.69   527.2  3762.9   563.6 3763.26     600 3766.51   629.6 3770.28
#Mann= 6 ,-1,0
       0      .1       0   206.6    .045       0   237.2      .1       0
  384.78     .12       0  434.78      .1       0  542.19     .12       0
#XS Ineff= 2 , 0
                          302.97         3753.86
Permanent Ineff=
       F       F
Bank Sta=206.6,237.2
XS Rating Curve= 0 ,0
Exp/Cntr(USF)=0,0
Exp/Cntr=0.3,0.1

Type RM Length L Ch R = 1 ,2878    ,262.1,269.9,290.9
XS GIS Cut Line= 2
2274488.85550071547092.8806406252274931.14710604546493.060518321
#Sta/Elev= 30
       0 3762.63    32.6 3762.67   113.4 3758.87   136.6 3755.87   143.8 3754.38
   163.6 3748.47   180.8 3746.32   196.7 3745.43   223.3 3746.25   245.3 3748.57
   292.9  3749.4     314 3747.82   345.4 3747.86   389.8 3750.69   430.2 3749.85
   450.4 3750.21   461.8 3747.84   465.6  3747.8   479.9 3749.15   501.6 3749.23
   506.6 3749.83   511.5 3751.26   556.3  3779.4     565 3783.25   574.3 3784.44
   617.2 3792.59   625.8 3795.21   645.8 3799.49   665.6    3806   745.3 3824.66
#Mann= 7 ,-1,0
       0      .1       0   180.8    .045       0   223.3      .1       0
     280     .12       0     450      .1       0     530     .12       0
     660      .1       0
#XS Ineff= 2 , 0
                          270.01         3754.95
Permanent Ineff=
       F       F
Bank Sta=180.8,223.3
XS Rating Curve= 0 ,0
Exp/Cntr(USF)=0,0
Exp/Cntr=0.3,0.1

Type RM Length L Ch R = 1 ,2608    ,84.2,84.3,85.5
XS GIS Cut Line= 4
2274527.91327851547091.6866999152274678.88540759547120.523228277
2274851.70314189547110.9003910392275085.69268964547010.338943908
#Sta/Elev= 30
       0 3760.13    20.6 3757.61    65.4  3754.4    81.7 3753.49      98 3753.64
   118.4 3751.65   130.6 3751.64     163 3747.74     179 3747.65     191 3746.07
   227.1 3745.07   231.1 3744.33   239.1 3745.58   251.1 3745.61   270.3 3743.15
   279.2 3742.19   287.2 3742.22   291.5 3743.15   295.2  3745.4   303.2 3753.49
   319.2 3763.12   334.5 3771.14   353.4 3777.63   383.9 3784.75   446.6 3795.02
   468.5 3799.94   518.9 3809.42   531.9  3813.2   556.8 3822.55   581.5 3829.46
#Mann= 5 ,-1,0
       0      .1       0      30     .12       0   270.3    .045       0
   291.5     .12       0  436.79      .1       0
Bank Sta=270.3,291.5
XS Rating Curve= 0 ,0
Exp/Cntr(USF)=0,0
Exp/Cntr=0.3,0.1

Type RM Length L Ch R = 1 ,2523    ,180.7,209.8,229.8
XS GIS Cut Line= 4
2274515.11025354547102.9786224822274680.62988687547197.168100838
2274903.03765614 547198.373896292275126.01480233547108.853534332
#Sta/Elev= 30
       0 3760.66    24.2 3758.78      38 3757.04    81.6 3754.36   110.9 3751.53
   166.7 3749.22   189.9  3746.4     198 3747.24   209.9 3745.41     218  3744.9
     270 3745.59   297.4 3742.74     306 3741.91     326 3742.07  327.37 3742.76
     330 3744.12   342.8 3756.23     354    3764     410 3780.34   463.9 3790.83
   478.7  3794.7   487.4 3794.98   508.9 3799.41   562.3 3806.92   582.2 3810.37
   590.8 3810.96   599.2 3813.27   608.4  3814.3   641.5 3823.53   653.1 3827.97
#Mann= 5 ,-1,0
       0      .1       0      50     .12       0   297.4    .045       0
  327.37     .12       0  472.85      .1       0
Bank Sta=297.4,327.37
XS Rating Curve= 0 ,0
Exp/Cntr(USF)=0,0
Exp/Cntr=0.3,0.1

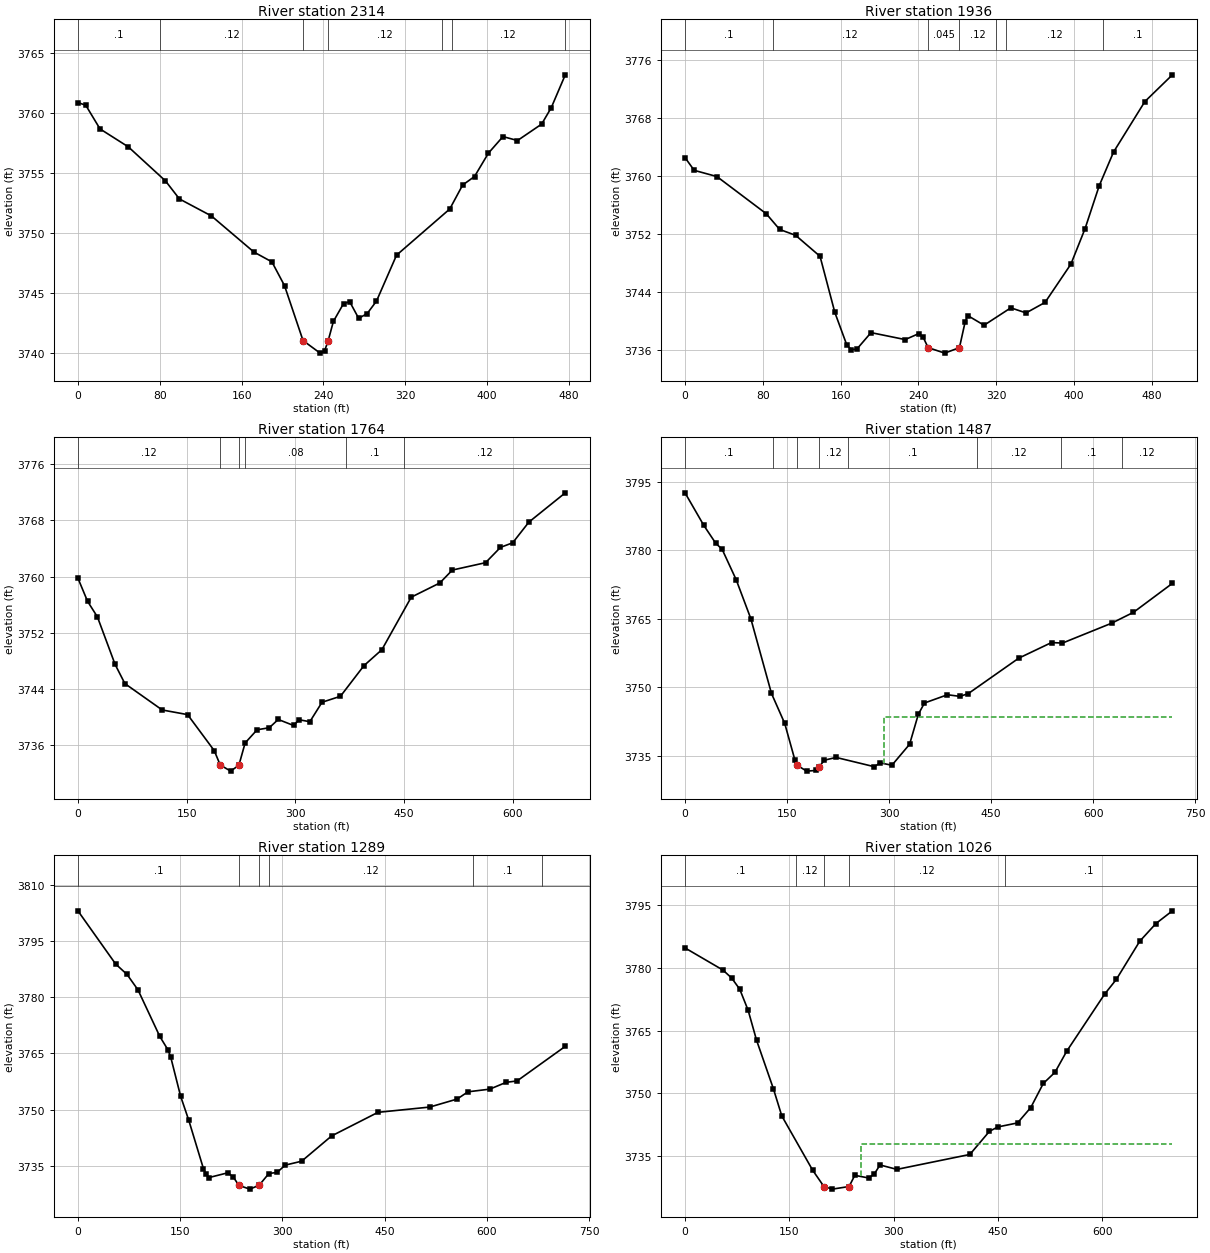
Type RM Length L Ch R = 1 ,2314    ,390.2,377.8,369.3
XS GIS Cut Line= 4
2274502.25471995547115.3911606882274655.24858666547242.245371775
2274681.38824228547303.750443817 2274859.7529512547415.997200293
#Sta/Elev= 30
       0 3760.87     7.7 3760.64    21.6 3758.67    49.3 3757.17    85.6 3754.33
    99.2 3752.83   130.5 3751.41     172  3748.4   189.6 3747.58   201.9  3745.6
     220 3741.02   236.7 3739.97     241 3740.15   244.4 3740.95   249.7 3742.62
   259.6  3744.1   265.6 3744.26   274.4 3742.87   282.7 3743.27   291.8 3744.31
   311.4 3748.14   363.4 3751.99     376 3753.99   387.6  3754.7   401.2 3756.65
   415.4 3758.03   429.6  3757.7   453.2 3759.07   462.6 3760.44   476.3 3763.18
#Mann= 7 ,-1,0
       0      .1       0      80     .12       0     220    .045       0
   244.4     .12       0  355.57      .1       0  365.57     .12       0
  475.57      .1       0
Bank Sta=220,244.4
XS Rating Curve= 0 ,0
Exp/Cntr(USF)=0,0
Exp/Cntr=0.3,0.1

Type RM Length L Ch R = 1 ,1936    ,167.2,171.6,178.5
XS GIS Cut Line= 2
2274283.64203051547392.8541094132274718.85467934547641.129781561
#Sta/Elev= 30
       0 3762.53     9.4 3760.77    32.8 3759.91    83.5 3754.78    97.3 3752.61
   113.7  3751.8   138.8  3748.9     154 3741.16   166.4 3736.63     171 3736.02
   176.6 3736.09   191.2 3738.37   226.3 3737.41   240.1 3738.22   244.7 3737.76
   249.9  3736.3     267 3735.54   282.1  3736.3     288 3739.88   290.7 3740.72
   307.4 3739.39   334.9 3741.79   350.6 3741.09   370.1 3742.54   396.7 3747.83
   411.2 3752.71   425.8 3758.65   440.5 3763.29   472.7 3770.26     501 3773.95
#Mann= 7 ,-1,0
       0      .1       0      90     .12       0   249.9    .045       0
   282.1     .12       0     320      .1       0     330     .12       0
     430      .1       0
Bank Sta=249.9,282.1
XS Rating Curve= 0 ,0
Exp/Cntr(USF)=0,0
Exp/Cntr=0.3,0.1

Type RM Length L Ch R = 1 ,1764    ,284.6,277.1,269
XS GIS Cut Line= 2
2274235.48582037547491.850590002 2274716.0245089547962.128665958
#Sta/Elev= 30
       0 3759.79    13.3 3756.49    26.9 3754.27    51.3  3747.5    64.8 3744.77
   116.3 3741.01   151.3 3740.35   188.1 3735.22   196.3 3733.18   210.7  3732.3
   222.1 3733.14   230.7 3736.31   247.2 3738.19     264 3738.48   276.4 3739.66
   297.6  3738.8     305 3739.62     320 3739.34   336.8 3742.11   362.2 3742.96
   394.6 3747.32   419.4  3749.6   459.9 3757.08   499.3  3759.1   516.6 3760.94
   562.4 3761.99     583 3764.17   599.8 3764.82   622.2 3767.77   672.4 3771.94
#Mann= 6 ,-1,0
       0     .12       0   196.3    .045       0   222.1     .12       0
     230     .08       0     370      .1       0     450     .12       0
Bank Sta=196.3,222.1
XS Rating Curve= 0 ,0
Exp/Cntr(USF)=0,0
Exp/Cntr=0.3,0.1

Type RM Length L Ch R = 1 ,1487    ,206.2,198.1,182
XS GIS Cut Line= 3
2274046.56389537547783.5825996422274456.54195877547951.209098467
 2274729.1874689547975.444254924
#Sta/Elev= 30
       0 3792.56    27.7 3785.41      45 3781.55    54.6 3780.18    75.2 3773.54
    96.8 3764.98   127.1 3748.63   146.6 3742.06   161.6 3734.03     165 3732.87
   178.9 3731.61   191.9 3731.75   197.4 3732.58   204.8    3734   222.1 3734.61
   278.3 3732.58     287 3733.42   304.2  3732.9   330.2 3737.49   343.1 3744.08
   352.1 3746.53   385.9 3748.34   404.3 3747.98   416.6  3748.6   490.7 3756.35
   538.9 3759.77   554.9 3759.65   627.3 3764.01   659.4 3766.39   716.6 3772.73
#Mann= 8 ,-1,0
       0      .1       0     130     .12       0     165    .045       0
   197.4     .12       0     240      .1       0     430     .12       0
  552.92      .1       0  642.92     .12       0
#XS Ineff= 2 , 0
                          293.05         3743.56
Permanent Ineff=
       F       F
Bank Sta=165,197.4
XS Rating Curve= 0 ,0
Exp/Cntr(USF)=0,0
Exp/Cntr=0.3,0.1

Type RM Length L Ch R = 1 ,1289    ,265.4,263.3,262.3
XS GIS Cut Line= 2
 2273984.1008125548028.8226476392274698.92348795548023.692341356
#Sta/Elev= 30
       0 3803.04    55.3 3788.85    72.1 3786.05    88.1 3781.94   120.1 3769.51
   132.1 3765.92   136.1 3764.01   150.6 3753.57   162.6 3747.13   184.1 3734.22
   188.1 3732.76   192.1 3731.83   220.1 3733.12   228.1 3731.91   236.1 3729.75
   252.1 3728.75   265.8 3729.78   280.1 3732.92   292.1 3733.21   304.1 3735.16
   328.1  3736.2   372.1 3742.95   440.1 3749.25   516.1 3750.66   556.1 3752.79
   572.1 3754.73   604.1 3755.44   628.1 3757.26   644.1 3757.63   714.8 3766.86
#Mann= 6 ,-1,0
       0      .1       0   236.1    .045       0   265.8      .1       0
     280     .12       0     580      .1       0     680     .12       0
Bank Sta=236.1,265.8
XS Rating Curve= 0 ,0
Exp/Cntr(USF)=0,0
Exp/Cntr=0.3,0.1

Type RM Length L Ch R = 1 ,1026    ,110.2,111,112.9
XS GIS Cut Line= 3
2274010.21116069548314.7364453182274502.99267531548248.089765062
2274696.87392696548310.697252575
#Sta/Elev= 30
       0  3784.8    54.5 3779.51    67.1  3777.6    78.7 3774.93    90.8 3769.88
   102.9 3762.73   127.1 3751.14   139.2 3744.63   183.6 3731.65   199.8 3727.75
   211.9 3727.13     2363727.753   244.2 3730.43   264.3 3729.79   272.4 3730.79
   280.5 3732.91   304.7 3731.85   409.7 3735.42   437.9 3740.96     450    3742
   478.3 3742.96   497.3 3746.63   515.3 3752.39   532.1 3755.06     549  3760.1
   603.6 3773.76   620.4 3777.28     654 3786.39   677.4 3790.64     701 3793.67
#Mann= 5 ,-1,0
       0      .1       0     160     .12       0   199.8    .045       0
     236     .12       0     460      .1       0
#XS Ineff= 2 , 0
                          252.63         3738.02
Permanent Ineff=
       F       F
Bank Sta=199.8,236
XS Rating Curve= 0 ,0
Exp/Cntr(USF)=0,0
Exp/Cntr=0.3,0.1

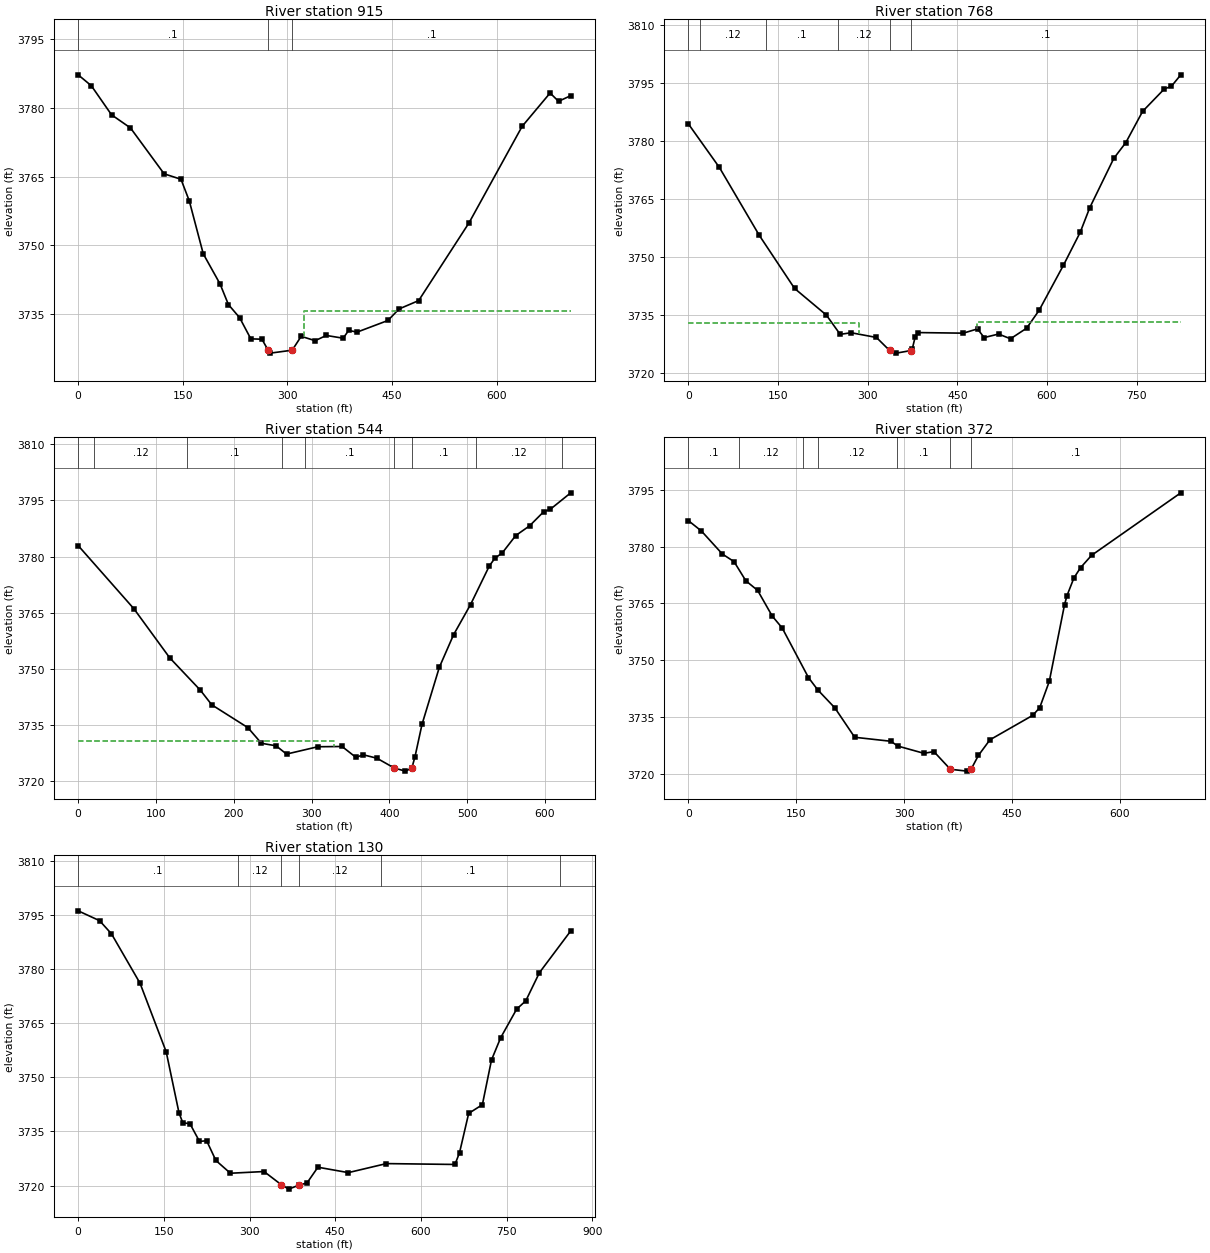
Type RM Length L Ch R = 1 ,915     ,157.7,146.7,131.9
XS GIS Cut Line= 2
 2273957.3145217548415.7109303452274661.67992285548365.844353273
#Sta/Elev= 30
       0 3787.17    18.9 3784.79    47.8 3778.47      75  3775.6   123.2 3765.61
   147.4 3764.42   159.3 3759.71   179.3 3748.19   203.4 3741.62   215.4 3737.13
   231.4 3734.29   247.5 3729.67   263.4 3729.59   272.2 3727.23   275.5 3726.56
   306.8  3727.2   319.7 3730.22   339.7 3729.27   355.7 3730.41   379.8 3729.81
   387.8  3731.5   399.9 3731.14     444 3733.67     460 3736.18   488.1    3738
   560.3 3754.94   636.4 3775.94   676.5 3783.21   688.6  3781.4   706.1 3782.63
#Mann= 3 ,-1,0
       0      .1       0   272.2    .045       0   306.8      .1       0
#XS Ineff= 2 , 0
                          323.37         3735.77
Permanent Ineff=
       F       F
Bank Sta=272.2,306.8
XS Rating Curve= 0 ,0
Exp/Cntr(USF)=0,0
Exp/Cntr=0.3,0.1

Type RM Length L Ch R = 1 ,768     ,195.9,223.4,260
BEGIN DESCRIPTION:
Embankment (structure/crossing artifact)
END DESCRIPTION:
XS GIS Cut Line= 5
2273957.10694433548443.2505716732274177.35099307548592.850302889
2274274.00211571548520.6407289232274329.54101593548440.866672252
2274667.82340814548470.150819638
#Sta/Elev= 30
       0 3784.39    52.1 3773.08   118.8 3755.54   177.8 3741.82     231 3734.93
   254.1 3729.95   272.4 3730.37   314.7 3729.15   336.6  3725.8   348.1  3725.1
   372.4 3725.77   374.6 3726.18   379.6 3729.35   384.6 3730.41   459.9 3730.26
   483.7 3731.36   494.8 3729.12   518.9 3730.03   538.9 3728.81   565.8 3731.54
   586.6 3736.13   627.3 3747.78   655.4 3756.31   671.4 3762.68   711.6 3775.43
   731.7  3779.5   759.8 3787.57   795.9 3793.34   807.9 3794.05   823.6 3797.01
#Mann= 6 ,-1,0
       0      .1       0      20     .12       0     130      .1       0
     250     .12       0   336.6    .045       0   372.4      .1       0
#XS Ineff= 2 , 0
          286.01 3732.81  482.38         3733.26
Permanent Ineff=
       F       F
Bank Sta=336.6,372.4
XS Rating Curve= 0 ,0
Exp/Cntr(USF)=0,0
Exp/Cntr=0.5,0.3

Type RM Length L Ch R = 1 ,544     ,173.9,172.3,171.6
XS GIS Cut Line= 3
2273956.03243588548457.1974974152274161.24468721548602.556175437
2274330.54479455548944.576594313
#Sta/Elev= 30
       0 3782.93    71.8 3765.99   117.7  3752.9     157 3744.26   171.7 3740.34
   218.2 3734.22   235.5 3730.05   254.4 3729.37   267.8 3727.16     308 3729.12
   339.2 3729.19   357.1 3726.26   366.3 3726.98     384 3726.05   406.2 3723.44
   420.4  3722.6   428.8 3723.38   432.9 3726.44   441.9 3735.08   464.2 3750.37
   482.5 3759.08   504.3 3767.14   528.6 3777.54   535.6 3779.54   545.2    3781
   562.4 3785.61   580.2 3788.21   598.1 3791.94     607 3792.67   633.1 3797.04
#Mann= 9 ,-1,0
       0      .1       0      20     .12       0     140      .1       0
  261.48     .12       0  291.48      .1       0   406.2    .045       0
   428.8      .1       0  511.48     .12       0  621.48      .1       0
#XS Ineff= 2 , 0
           329.3 3730.63
Permanent Ineff=
       F       F
Bank Sta=406.2,428.8
XS Rating Curve= 0 ,0
Exp/Cntr(USF)=0,0
Exp/Cntr=0.3,0.1

Type RM Length L Ch R = 1 ,372     ,242.6,242.6,242.6
XS GIS Cut Line= 3
2273889.02125296548483.2787038162274140.72346208548932.605879652
2274296.27693643549000.279607751
#Sta/Elev= 30
       0 3786.88    18.4  3784.1    47.4 3778.04    63.7 3776.02    80.1 3770.97
    96.5 3768.42   116.8 3761.64   130.6 3758.51   167.2 3745.39     180 3742.17
   203.9 3737.39   231.4 3729.64   281.9 3728.58     291 3727.34   327.7  3725.4
   341.5 3725.86   364.4 3721.19   387.3  3720.7  393.31 3721.23   403.4 3724.85
   419.4 3728.97     479 3735.44   488.6 3737.46   501.9 3744.39   523.1 3764.65
   526.5 3767.03   536.2 3771.74   545.4 3774.43   560.6 3777.67   684.7 3794.19
#Mann= 7 ,-1,0
       0      .1       0      70     .12       0     160      .1       0
     180     .12       0     290      .1       0   364.4    .045       0
  393.31      .1       0
Bank Sta=364.4,393.31
XS Rating Curve= 0 ,0
Exp/Cntr(USF)=0,0
Exp/Cntr=0.3,0.1

Type RM Length L Ch R = 1 ,130     ,,,
XS GIS Cut Line= 4
2273721.40887958548569.2055881142273802.19273443548847.909887366
2273953.66246229549037.7519462772274282.85667083 549041.79113902
#Sta/Elev= 30
       0 3796.08    37.5 3793.35    58.3 3789.71   108.3 3776.03   154.1 3757.04
   176.6 3740.08   183.2 3737.39   195.7 3737.13   212.4 3732.23   224.9 3732.42
   241.1 3726.95   266.5 3723.42   325.4 3723.89   355.1  3720.3   368.6 3719.02
   386.83720.146   400.6 3720.73   419.7 3725.09   472.9 3723.59   539.6 3726.09
   659.6 3725.85   667.6  3729.1   683.6 3739.99   707.6  3742.4   723.6  3754.8
   739.6 3760.93   767.6 3768.86   783.6 3771.16   807.5 3778.96   862.3 3790.52
#Mann= 6 ,-1,0
       0      .1       0     280     .12       0   355.1    .045       0
   386.8     .12       0  530.18      .1       0  843.04     .12       0
Bank Sta=355.1,386.8
XS Rating Curve= 0 ,0
Exp/Cntr(USF)=0,0
Exp/Cntr=0.3,0.1
LCMann Table=0

Chan Stop Cuts=-1
Use User Specified Reach Order=0
Composite Channel Slope=5